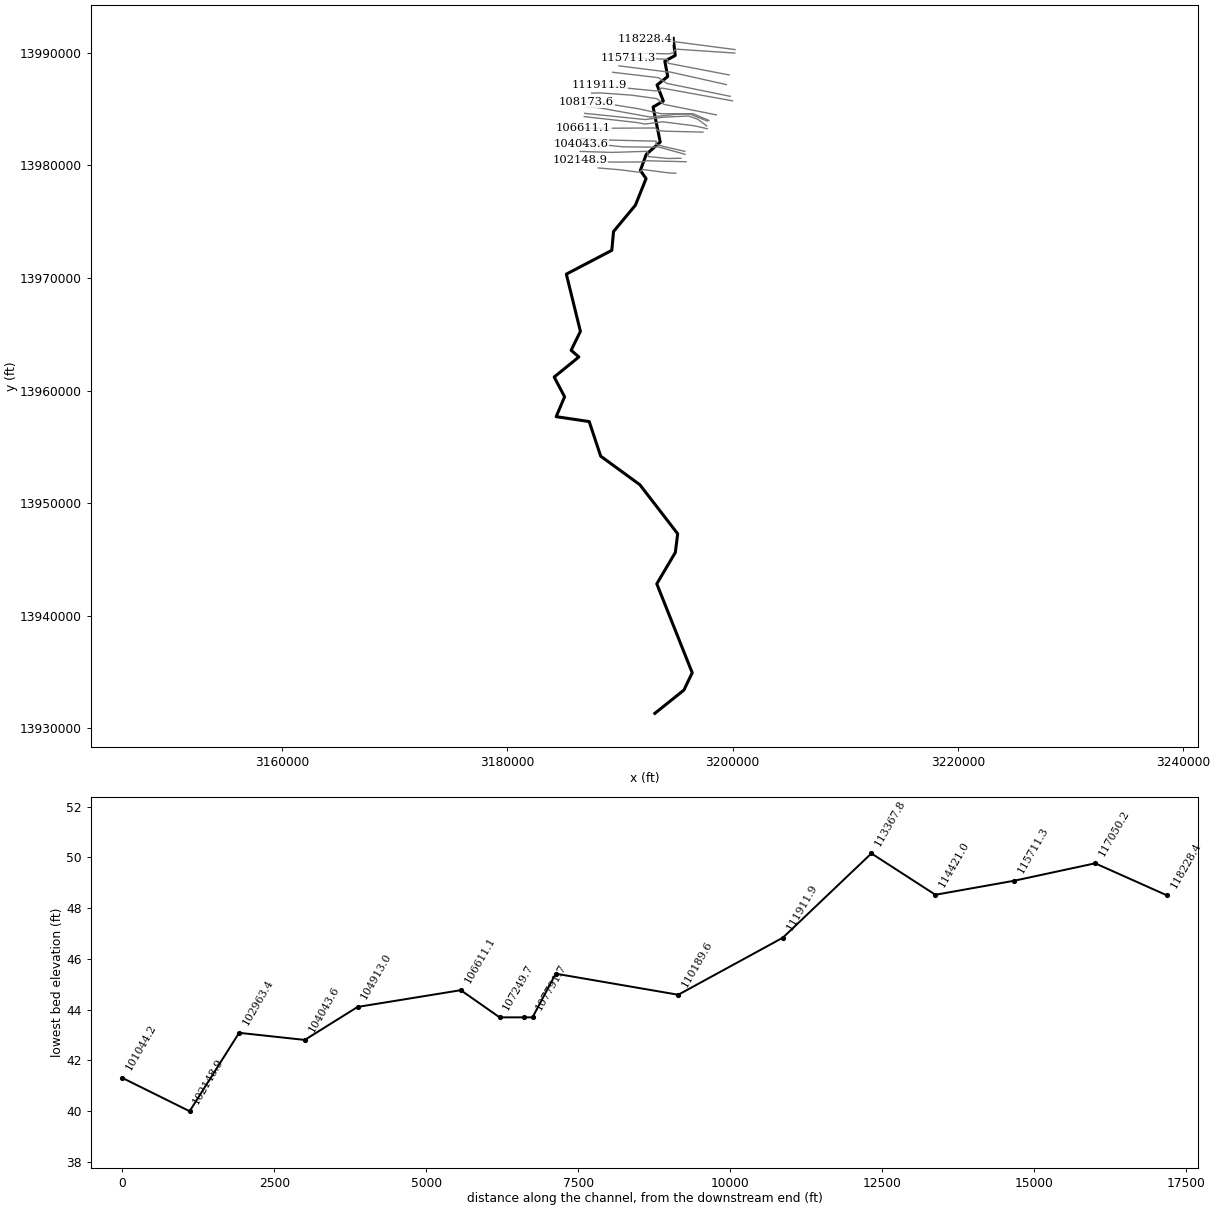
--- G103-80-00.prj (project) ---

Proj Title=G103-80-00
Current Plan=p01
Default Exp/Contr=.3,.1
English Units
Geom File=g03
Flow File=f02
Flow File=f01
Plan File=p02
Plan File=p01
Y Axis Title=Elevation
X Axis Title(PF)=Main Channel Distance
X Axis Title(XS)=Station
BEGIN DESCRIPTION:
San Jacinto River Watershed
East Fork San Jacinto River
HCFCD unit G103-80-00
(Flood Hazard, Floodway)Model
10, 2, 1, 0.2% Event
Filename G1038000.prj
Prepared by:  FTN Associates Ltd.   DATE:  February 2003
Reviewed by:     DATE:
STATUS (Final)
The boundary condition is known water surface elevation at the downstream end, obtained from the Lake Houston model. WSEl of 45.87, 48.57, 50.01, 54.16 are used for the 10, 50, 100 and 500yr profiles respectively.
section 51110.17 is a common section for Lake houston and EF San jacincto to obtain the WSELs from the Lake Houston model as the boundary condition.
7 most upstream XS were trimmed on ROB b/c no tin data was available.  This did not cause any problem with the 2% annual chance flood extending out of the cross section limits.
The known water surface elevation of 50.90' comes from the computed floodway elevation  of Lake Houston at the common section.
END DESCRIPTION:
DSS Export Rating Curves= 0
DSS Export Rating Curve Sorted= 0
DSS Export Volume Flow Curves= 0
DXF OffsetX= 0
DXF OffsetY= 0
DXF ScaleX= 1
DXF ScaleY= 10

--- G103-80-00.p01 (plan) ---

Plan Title=Floodway
Version=Version 3.0.1  Mar 2001
Short Identifier=Floodway0607
Geom File=g03
Flow File=f02
Subcritical Flow
K Sum by GR= 0
Std Step Tol= 0.01
Critical Tol= 0.01
Num of Std Step Trials= 20
Max Error Tol= 0.3
Flow Tol Ratio= 0.001
Split Flow NTrial= 30
Split Flow Tol= 0.02
Split Flow Ratio= 0.02
Log Output Level= 0
Friction Slope Method= 1
Unsteady Friction Slope Method= 2
Parabolic Critical Depth
Global Vel Dist= 0 , 0 , 0
Global Log Level= 0
CheckData=True
Encroach Param=-1 ,0,0, 2
Encroach River=G103-80-00
Encroach Reach=EF San Jacinto
Encroach Node=118228.4
       1    3910    5873
Encroach Node=117050.2
       1    4290    6475
Encroach Node=115711.3
       1    4947    6286
Encroach Node=114421.0
       1    4653    6019
Encroach Node=113367.8
       1    4866    6459
Encroach Node=111911.9
       1    5388 7118.98
Encroach Node=110189.6
       1    3707 6140.76
Encroach Node=108173.6
       1  4527.5 5771.44
Encroach Node=107791.7
       1    4540    5800
Encroach Node=107721.3
       1    4540    5800
Encroach Node=107651.0
       1    4540    5800
Encroach Node=107249.7
       1    3843    5567
Encroach Node=106611.1
       1    3468    5402
Encroach Node=104913.0
       1    2283    4445
Encroach Node=104043.6
       1    2427    4387
Encroach Node=102963.4
       1    2489    4667
Encroach Node=102148.9
       1    2277    4052
Encroach Node=101044.2
       1    2559    3894
Encroach Node=100130.0
       1    2596    3740
Encroach Node=98845.11
       1    2560    4127
Encroach Node=97707.19
       1    2745    3956
Encroach Node=96828.22
       1    2357    3500
Encroach Node=95509.50
       1    2700    4500
Encroach Node=94407.89
       1    2545    3780
Encroach Node=92882.15
       1    1990    3137
Encroach Node=91343.42
       1    1446    2527
Encroach Node=90087.30
       1    1790    3565
Encroach Node=88594.25
       1    2204    4195
Encroach Node=87213.89
       1    1820    3773
Encroach Node=85298.22
       1    2195    4250
Encroach Node=83946.74
       1     930    2539
Encroach Node=82583.35
       1    1000    2632
Encroach Node=81851.79
       1     640    3087
Encroach Node=80668.04
       1   908.1    2805
Encroach Node=79916.10
       1     910    1972
Encroach Node=78754.21
       1     655    2080
Encroach Node=77767.82
       1  502.97    2110
Encroach Node=76556.03
       1    1060    2785
Encroach Node=75526.59
       1    1500    3205
Encroach Node=74263.07
       1    2255    4395
Encroach Node=73434.88
       1    2420    3979
Encroach Node=71410.85
       1    1205    4150
Encroach Node=70314.34
       1    1420    4501
Encroach Node=68799.84
       1    1870    4150
Encroach Node=67491.99
       1    2000    3802
Encroach Node=66268.62
       1    2435    4205
Encroach Node=65134.80
       1    3415    4514
Encroach Node=63701.51
       1    3223    4603
Encroach Node=62736.58
       1    3305    5260
Encroach Node=61490.38
       1    2812    5236
Encroach Node=60012.01
       1    3451    5471
Encroach Node=56652.75
       1 2293.09    5512
Encroach Node=53751.67
       1    1000 5201.15
Encroach Node=51110.17
       1    1622 7241.44
Encroach Reach=G103-80-00_0511
Encroach Node=118228.4
       1    3910    5873
Encroach Node=117050.2
       1    4290    6475
Encroach Node=115711.3
       1    4947    6286
Encroach Node=114421.0
       1    4653    6019
Encroach Node=113367.8
       1    4866    6459
Encroach Node=111911.9
       1    5388 7118.98
Encroach Node=110189.6
       1    3707 6140.76
Encroach Node=108173.6
       1  4527.5 5771.44
Encroach Node=107791.7
       1    4540    5800
Encroach Node=107721.3
       1    4540    5800
Encroach Node=107651.0
       1    4540    5800
Encroach Node=107249.7
       1    3843    5567
Encroach Node=106611.1
       1    3468    5402
Encroach Node=104913.0
       1    2283    4445
Encroach Node=104043.6
       1    2427    4387
Encroach Node=102963.4
       1    2489    4667
Encroach Node=102148.9
       1    2277    4052
Encroach Node=101044.2
       1    2559    3894
Encroach Node=100130.0
       1    2596    3740
Encroach Node=98845.11
       1    2560    4127
Encroach Node=97707.19
       1    2745    3956
Encroach Node=96828.22
       1    2357    3500
Encroach Node=95509.50
       1    2700    4500
Encroach Node=94407.89
       1    2545    3780
Encroach Node=92882.15
       1    1990    3137
Encroach Node=91343.42
       1    1446    2527
Encroach Node=90087.30
       1    1790    3565
Encroach Node=88594.25
       1    2204    4195
Encroach Node=87213.89
       1    1820    3773
Encroach Node=85298.22
       1    2195    4250
Encroach Node=83946.74
       1     930    2539
Encroach Node=82583.35
       1    1000    2632
Encroach Node=81851.79
       1     640    3087
Encroach Node=80668.04
       1   908.1    2805
Encroach Node=79916.10
       1     910    1972
Encroach Node=78754.21
       1     655    2080
Encroach Node=77767.82
       1  502.97    2110
Encroach Node=76556.03
       1    1060    2785
Encroach Node=75526.59
       1    1500    3205
Encroach Node=74263.07
       1    2255    4395
Encroach Node=73434.88
       1    2420    3979
Encroach Node=71410.85
       1    1205    4150
Encroach Node=70314.34
       1    1420    4501
Encroach Node=68799.84
       1    1870    4150
Encroach Node=67491.99
       1    2000    3802
Encroach Node=66268.62
       1    2435    4205
Encroach Node=65134.80
       1    3415    4514
Encroach Node=63701.51
       1    3223    4603
Encroach Node=62736.58
       1    3305    5260
Encroach Node=61490.38
       1    2812    5236
Encroach Node=60012.01
       1    3451    5471
Encroach Node=56652.75
       1 2293.09    5512
Encroach Node=53751.67
       1    1000 5201.15
Encroach Node=51110.17
       1    1622 7241.44
Computation Interval=1HOUR
Output Interval=1HOUR
Run HTab= 0
Run UNet= 0
Run PostProcess= 0
UNET Theta= 1
UNET ZTol= 0.02
UNET ZSATol= 0.1
UNET MxIter= 20
UNET MaxInSteps= 20
UNET DtIC= 0
UNET DtMin= 0
UNET MaxCRTS= 20
UNET WFStab= 2
UNET SFStab= 1
UNET WFX= 1
UNET SFX= 1
UNET Convert EG Bridges=-1
UNET Use Existing IB Tables=-1
Instantaneous Interval=1HOUR
Write IC File= 0
IC Time=0
Write Velocity= 0
Write Detailed= 0

--- G103-80-00.p02 (plan) ---

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Plan Title=FEMA Effective June 2007
Short Identifier=FEMAeff0607
Geom File=g03
Flow File=f01

--- G103-80-00.f02 (steady flow) ---

Flow Title=Floodway
Version=Version 3.0.1  Mar 2001
Number of Profiles= 2
Profile Names=1PCT_100yr, 1PCTFloodway_100yrFW
River Rch & RM=G103-80-00,G103-80-00_0511        ,118228.4
   34200   34200
River Rch & RM=G103-80-00,G103-80-00_0511        ,104043.6
   34253   34253
River Rch & RM=G103-80-00,G103-80-00_0511        ,102148.9
   34357   34357
River Rch & RM=G103-80-00,G103-80-00_0511        ,98845.11
   34431   34431
River Rch & RM=G103-80-00,G103-80-00_0511        ,96828.22
   34476   34476
River Rch & RM=G103-80-00,G103-80-00_0511        ,95509.50
   34504   34504
River Rch & RM=G103-80-00,G103-80-00_0511        ,94407.89
   34529   34529
River Rch & RM=G103-80-00,G103-80-00_0511        ,92882.15
   34570   34570
River Rch & RM=G103-80-00,G103-80-00_0511        ,91343.42
   34655   34655
River Rch & RM=G103-80-00,G103-80-00_0511        ,88594.25
   34728   34728
River Rch & RM=G103-80-00,G103-80-00_0511        ,87213.89
   34786   34786
River Rch & RM=G103-80-00,G103-80-00_0511        ,85298.22
   34877   34877
River Rch & RM=G103-80-00,G103-80-00_0511        ,81851.79
   34919   34919
River Rch & RM=G103-80-00,G103-80-00_0511        ,80668.04
   34981   34981
River Rch & RM=G103-80-00,G103-80-00_0511        ,78754.21
   35004   35004
River Rch & RM=G103-80-00,G103-80-00_0511        ,77767.82
   35097   35097
River Rch & RM=G103-80-00,G103-80-00_0511        ,74263.07
   35137   35137
River Rch & RM=G103-80-00,G103-80-00_0511        ,73434.88
   35200   35200
River Rch & RM=G103-80-00,G103-80-00_0511        ,71410.85
  108500  108500
River Rch & RM=G103-80-00,G103-80-00_0511        ,70314.34
  108584  108584
River Rch & RM=G103-80-00,G103-80-00_0511        ,68799.84
  108634  108634
River Rch & RM=G103-80-00,G103-80-00_0511        ,67491.99
  108651  108651
River Rch & RM=G103-80-00,G103-80-00_0511        ,66268.62
  108727  108727
River Rch & RM=G103-80-00,G103-80-00_0511        ,65134.80
  109075  109075
River Rch & RM=G103-80-00,G103-80-00_0511        ,60012.01
  109182  109182
River Rch & RM=G103-80-00,G103-80-00_0511        ,56652.75
  109500  109500
River Rch & RM=G103-80-00,G103-80-00_0511        ,53751.67
  121700  121700
River Rch & RM=G103-80-00,G103-80-00_0511        ,51110.17
  121724  121724
Boundary for River Rch & Prof#=G103-80-00,G103-80-00_0511        , 1
Up Type= 0
Dn Type= 1
Dn Known WS=50.01
Boundary for River Rch & Prof#=G103-80-00,G103-80-00_0511        , 2
Up Type= 0
Dn Type= 1
Dn Known WS=50.9
DSS Import GetInterval= 0
DSS Import GetPeak= 0
DSS Import FillOption= 0

--- G103-80-00.f01 (steady flow) ---

Flow Title=FEMA Effective June 2007
Version=Version 3.0.1  Mar 2001
Number of Profiles= 4
Profile Names=10PCT_10yr, 2PCT_50yr, 1PCT_100yr, 0.2PCT_500yr
River Rch & RM=G103-80-00,G103-80-00_0511        ,118228.4
   10500   24500   34200   66100
River Rch & RM=G103-80-00,G103-80-00_0511        ,104043.6
   10527   24553   34253   66127
River Rch & RM=G103-80-00,G103-80-00_0511        ,102148.9
   10578   24657   34357   66178
River Rch & RM=G103-80-00,G103-80-00_0511        ,98845.11
   10611   24731   34431   66215
River Rch & RM=G103-80-00,G103-80-00_0511        ,96828.22
   10638   24776   34476   66238
River Rch & RM=G103-80-00,G103-80-00_0511        ,95509.50
   10652   24804   34504   66252
River Rch & RM=G103-80-00,G103-80-00_0511        ,94407.89
   10665   24829   34529   66265
River Rch & RM=G103-80-00,G103-80-00_0511        ,92882.15
   10685   24870   34570   66285
River Rch & RM=G103-80-00,G103-80-00_0511        ,91343.42
   10727   24955   34655   66327
River Rch & RM=G103-80-00,G103-80-00_0511        ,88594.25
   10764   25028   34728   66364
River Rch & RM=G103-80-00,G103-80-00_0511        ,87213.89
   10793   25086   34786   66393
River Rch & RM=G103-80-00,G103-80-00_0511        ,85298.22
   10839   25177   34877   66439
River Rch & RM=G103-80-00,G103-80-00_0511        ,81851.79
   10860   25219   34919   66460
River Rch & RM=G103-80-00,G103-80-00_0511        ,80668.04
   10890   25281   34981   66490
River Rch & RM=G103-80-00,G103-80-00_0511        ,78754.21
   10902   25304   35004   66502
River Rch & RM=G103-80-00,G103-80-00_0511        ,77767.82
   10948   25397   35097   66548
River Rch & RM=G103-80-00,G103-80-00_0511        ,74263.07
   10969   25437   35137   66569
River Rch & RM=G103-80-00,G103-80-00_0511        ,73434.88
   11000   25500   35200   66600
River Rch & RM=G103-80-00,G103-80-00_0511        ,71410.85
   41300   84400  108500  182800
River Rch & RM=G103-80-00,G103-80-00_0511        ,70314.34
   41308   84467  108584  182984
River Rch & RM=G103-80-00,G103-80-00_0511        ,68799.84
   41313   84507  108634  183094
River Rch & RM=G103-80-00,G103-80-00_0511        ,67491.99
   41315   84520  108651  183131
River Rch & RM=G103-80-00,G103-80-00_0511        ,66268.62
   41323   84582  108727  183300
River Rch & RM=G103-80-00,G103-80-00_0511        ,65134.80
   41358   84860  109075  184066
River Rch & RM=G103-80-00,G103-80-00_0511        ,60012.01
   41369   84946  109182  184301
River Rch & RM=G103-80-00,G103-80-00_0511        ,56652.75
   41400   85200  109500  185000
River Rch & RM=G103-80-00,G103-80-00_0511        ,53751.67
   42700   94300  121700  211500
River Rch & RM=G103-80-00,G103-80-00_0511        ,51110.17
   42935   94300  121724  211500
Boundary for River Rch & Prof#=G103-80-00,G103-80-00_0511        , 1
Up Type= 0
Dn Type= 1
Dn Known WS=45.67
Boundary for River Rch & Prof#=G103-80-00,G103-80-00_0511        , 2
Up Type= 0
Dn Type= 1
Dn Known WS=48.57
Boundary for River Rch & Prof#=G103-80-00,G103-80-00_0511        , 3
Up Type= 0
Dn Type= 1
Dn Known WS=50.01
Boundary for River Rch & Prof#=G103-80-00,G103-80-00_0511        , 4
Up Type= 0
Dn Type= 1
Dn Known WS=54.16
DSS Import GetInterval= 0
DSS Import GetPeak= 0
DSS Import FillOption= 0

--- G103-80-00.g03 (geometry) ---

Geom Title=G103-80-00 June 2007
Version=Version 3.0.1  Mar 2001

River Reach=G103-80-00      ,G103-80-00_0511
Reach XY= 30
     3194722.432    13991284.845     3194903.193    13989767.059
     3193975.332    13989255.349     3194237.151    13987893.742
     3193285.057    13987143.777     3193845.887    13985715.405
     3192934.912    13985183.952     3193567.968     13982073.73
     3192325.671    13980973.505     3191804.923    13979551.604
       3192311.2    13978824.613     3191362.801    13976463.337
     3189420.652    13974124.522     3189268.037    13972454.355
     3185228.287    13970340.315     3186479.114     13965257.42
     3185655.669    13963577.603     3186340.231    13962983.869
     3184149.661    13961198.578     3185074.389    13959448.138
     3184327.178    13957681.955     3187261.367    13957245.023
     3188279.774    13954174.313      3191760.17    13951634.199
     3195119.346    13947279.426     3194909.334     13945616.62
     3193263.117    13942833.672     3196409.017    13934935.456
     3195672.742    13933395.973     3193088.369    13931326.274

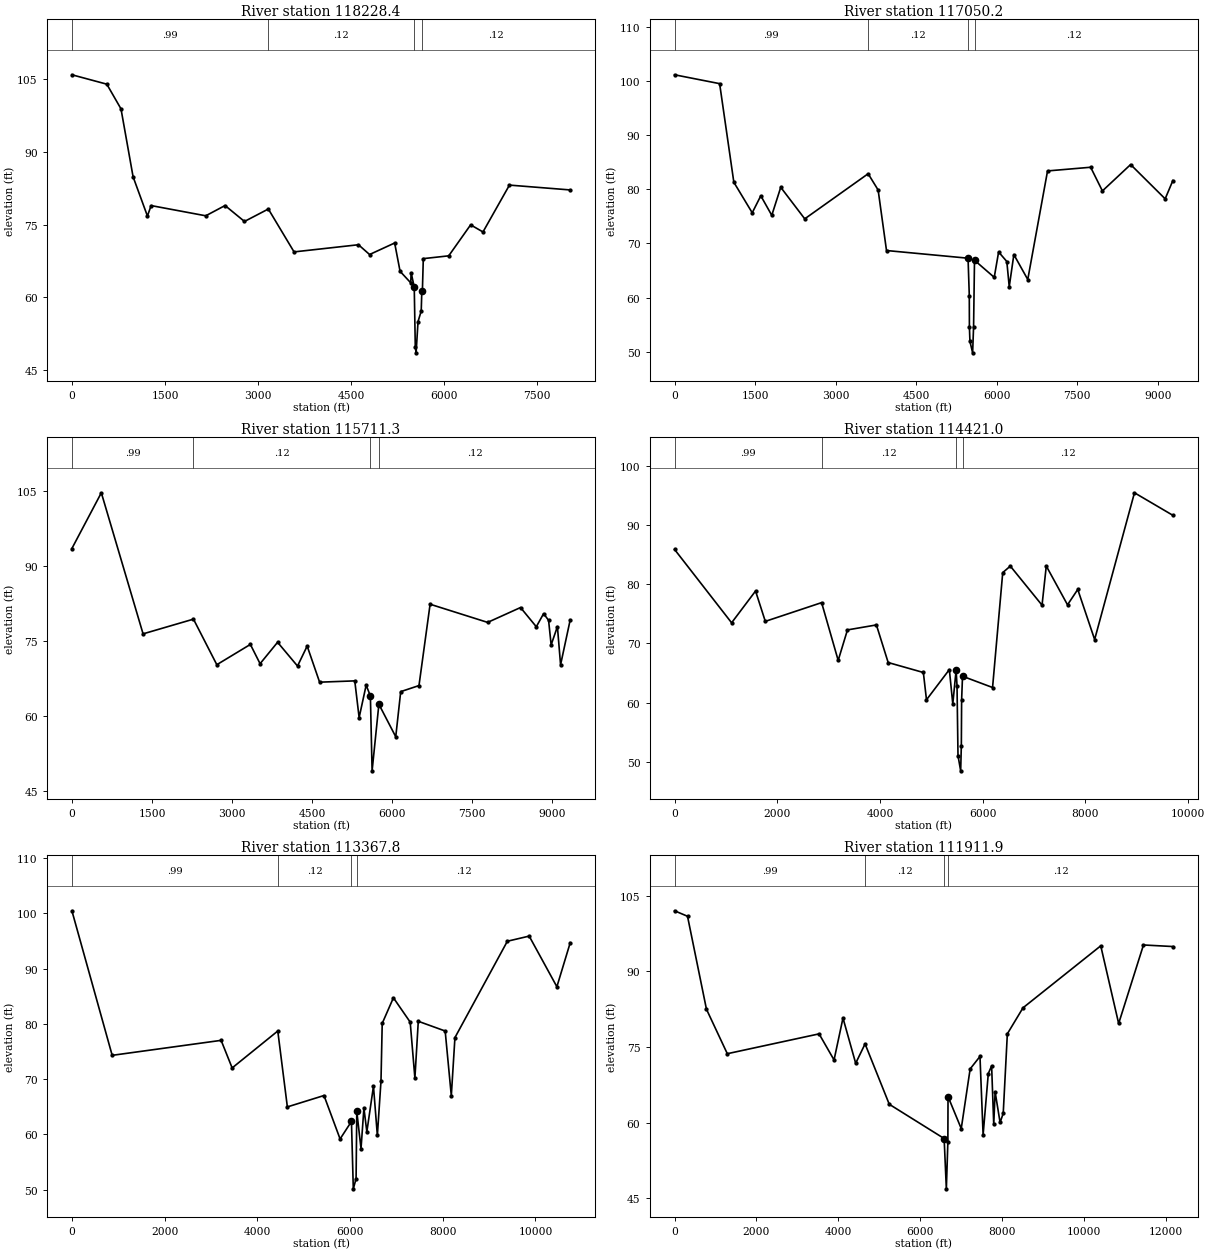
Type RM Length L Ch R = 1 ,118228.4,623.3,1178.23,1329.76
BEGIN DESCRIPTION:
411v1
Bank Station offset =      -548
Cross section trimmed on ROB due to lack of TIN data; considered limit of study.
END DESCRIPTION:
XS GIS Cut Line= 6
     3200216.884    13990286.697     3194958.663     13990971.19
     3194811.808    13991003.226     3194540.122    13991074.235
     3193931.909    13991166.143     3192248.808     13991190.54
#Sta/Elev= 30
       0  105.95  562.57  104.01  791.35   98.91  986.47   84.87 1217.43   76.77
 1276.99   78.93 2157.61   76.82 2468.76   78.94  2781.7   75.65 3166.23   78.22
 3580.81   69.36 4618.92   70.84 4798.09   68.82 5202.35    71.2 5289.77   65.35
 5461.83   62.97 5468.05   65.06 5518.05   62.11 5535.05   49.71 5548.05   48.51
 5579.05   54.96 5630.55   57.15 5640.05   61.27 5649.05   61.11 5664.05   67.97
 6073.86   68.55 6426.85   74.95 6625.92   73.48 7052.42   83.16  8032.1   82.16
#Mann= 4 ,-1 , 0
       0     .99       0 3166.23     .12       0 5518.05     .05       0
 5640.05     .12       0
Bank Sta=5518.05,5640.05
XS Rating Curve= 0
Exp/Cntr=.3,.1

Type RM Length L Ch R = 1 ,117050.2,1466.26,1338.81,539.28
BEGIN DESCRIPTION:
411v2
Bank Station offset =      -551
Cross section trimmed on ROB due to lack of TIN data; considered limit of study.
END DESCRIPTION:
XS GIS Cut Line= 6
     3200194.669    13989975.681     3195061.883    13990320.922
     3194830.332    13990234.477     3194737.712    13990002.926
     3194334.812    13989905.445     3191112.079     13989978.03
#Sta/Elev= 30
       0  101.19  839.63   99.55 1104.31   81.31 1446.73   75.67 1606.37   78.81
 1810.78    75.2 1977.74   80.38 2424.81   74.55 3605.66   82.89 3791.61   79.88
 3947.47   68.69 5466.31   67.27 5489.31   60.34 5491.31   54.59 5501.31   51.89
 5551.31   49.77 5569.31   54.64 5586.31   66.89 5953.84   63.73 6035.36   68.42
 6188.16   66.66 6233.18   61.99 6319.22   67.94 6578.26   63.33 6946.68   83.41
 7749.34   84.09 7968.38   79.71 8493.86   84.59 9137.14   78.25 9280.65   81.63
#Mann= 4 ,-1 , 0
       0     .99       0 3605.66     .12       0 5466.31     .05       0
 5586.31     .12       0
#Block Obstruct= 2 , 0
       0                    6960       0      83
Bank Sta=5466.31,5586.31
XS Rating Curve= 0
Exp/Cntr=.3,.1

Type RM Length L Ch R = 1 ,115711.3,772.98,1290.35,1116.57
BEGIN DESCRIPTION:
411v3
Bank Station offset =      -623
Cross section trimmed on ROB due to lack of TIN data; considered limit of study.
END DESCRIPTION:
XS GIS Cut Line= 6
      3199689.53    13988033.893     3194334.812    13989060.647
     3194265.348    13989085.984     3194204.843    13989411.563
     3194061.878     13989424.56     3190731.951     13989576.91
#Sta/Elev= 30
       0   93.49  551.38  104.62 1333.28   76.44 2277.16   79.38 2714.64   70.28
    3343   74.33 3524.95   70.48 3852.89   74.76 4226.36   70.01 4406.94      74
 4640.18   66.79  5298.7   67.05 5380.34   59.71 5511.91   66.19 5591.26   64.03
 5623.26   49.08 5750.26   62.38  6066.2   55.89 6159.18    64.9 6501.44   66.11
 6709.79   82.36 7787.42   78.73 8403.39    81.7 8699.37   77.86 8835.76   80.48
 8929.11   79.15 8977.05   74.24 9094.48   77.89 9153.77   70.27 9334.33   79.25
#Mann= 4 ,-1 , 0
       0     .99       0 2277.16     .12       0 5591.26     .05       0
 5750.26     .12       0
#Block Obstruct= 2 , 0
       0                    6750       0    82.5
Bank Sta=5591.26,5750.26
XS Rating Curve= 0
Exp/Cntr=.3,.1

Type RM Length L Ch R = 1 ,114421.0,1061.25,1053.18,681.34
BEGIN DESCRIPTION:
411v4
Bank Station offset =      -570
Cross section trimmed on ROB due to lack of TIN data; considered limit of study.
END DESCRIPTION:
XS GIS Cut Line= 6
      3199442.59    13987176.098     3194451.784    13988293.831
      3194123.33    13988304.886     3193970.899    13988319.825
     3193853.927    13988345.818     3189899.569    13988841.302
#Sta/Elev= 30
       0   85.86 1110.88   73.49 1576.97   78.85 1766.88   73.73 2863.01   76.89
 3185.82   67.15 3366.18   72.29  3929.7   73.13 4158.81   66.79 4843.77   65.11
 4904.78   60.51 5349.83    65.6 5416.89   59.81 5481.26    65.5 5499.26   62.89
 5518.26   51.09 5570.26   48.53 5583.26   52.79 5588.76   60.47 5606.26   64.48
 6191.11   62.58  6389.1   81.95 6536.64   83.05  7154.3   76.46 7236.89   83.06
 7650.34   76.52 7849.65   79.11 8178.36   70.67 8953.69   95.41 9701.34   91.61
#Mann= 4 ,-1 , 0
       0     .99       0 2863.01     .12       0 5481.26     .05       0
 5606.26     .12       0
#Block Obstruct= 2 , 0
       0                    6540       0      84
Bank Sta=5481.26,5606.26
XS Rating Curve= 0
Exp/Cntr=.3,.1

Type RM Length L Ch R = 1 ,113367.8,491.19,1455.93,1197.78
BEGIN DESCRIPTION:
411v5
Bank Station offset =     -1071
Cross section trimmed on ROB due to lack of TIN data; considered limit of study.
END DESCRIPTION:
XS GIS Cut Line= 6
     3199780.509    13986136.347     3194165.853    13987280.074
     3193965.876    13987409.555     3193567.608    13987693.591
     3193419.415    13987789.299     3189331.205    13988272.938
#Sta/Elev= 30
       0  100.46  869.22   74.31 3219.18   77.02 3457.29   72.03 4441.73   78.71
 4648.39   64.98 5438.57   67.04 5785.98   59.18 6031.17   62.35 6071.17   50.16
 6131.17   52.01 6146.17   64.17 6237.51   57.44 6299.98   64.76  6363.2   60.47
 6505.98   68.72 6590.03   59.81 6668.44   69.67 6694.75   80.09 6936.35   84.72
 7298.28   80.32 7399.96   70.19 7473.03   80.47 8053.04   78.71  8185.4      67
 8263.71   77.52  9394.6   94.95 9865.35   95.8810463.03   86.7210750.75   94.68
#Mann= 4 ,-1 , 0
       0     .99       0 4441.73     .12       0 6031.17     .05       0
 6146.17     .12       0
#Block Obstruct= 2 , 0
       0                    6940       0      85
Bank Sta=6031.17,6146.17
XS Rating Curve= 0
Exp/Cntr=.3,.1

Type RM Length L Ch R = 1 ,111911.9,1392.15,1722.28,787.2
BEGIN DESCRIPTION:
411v6
Bank Station offset =     -1640
Cross section trimmed on ROB due to lack of TIN data; considered limit of study.
END DESCRIPTION:
XS GIS Cut Line= 6
     3199988.459    13985733.444     3193737.412    13986863.095
     3193552.171    13986838.396     3193558.346    13986631.544
     3193139.099    13986617.232     3188156.585    13987098.318
#Sta/Elev= 30
       0  102.05  316.89  100.96  779.82    82.5 1289.03   73.67 3530.96   77.61
 3896.79   72.43 4115.08   80.75 4425.39   71.77 4654.63   75.62    5246   63.63
 6586.45   56.83 6640.45   46.84 6677.45   56.12 6681.45   65.16 7004.31    58.8
 7221.89   70.65 7462.09   73.13 7538.49   57.57 7665.57   69.74 7746.51   71.25
 7798.28   59.62 7832.08    66.1 7953.18   60.02 8029.82   61.81 8130.71   77.62
    8513   82.7810412.46   95.0910850.18   79.6711456.31   95.2612174.59   94.95
#Mann= 4 ,-1 , 0
       0     .99       0 4654.63     .12       0 6586.45     .05       0
 6681.45     .12       0
#Block Obstruct= 2 , 0
       0                   10410       0    95.3
Bank Sta=6586.45,6681.45
XS Rating Curve= 0
Exp/Cntr=.3,.1

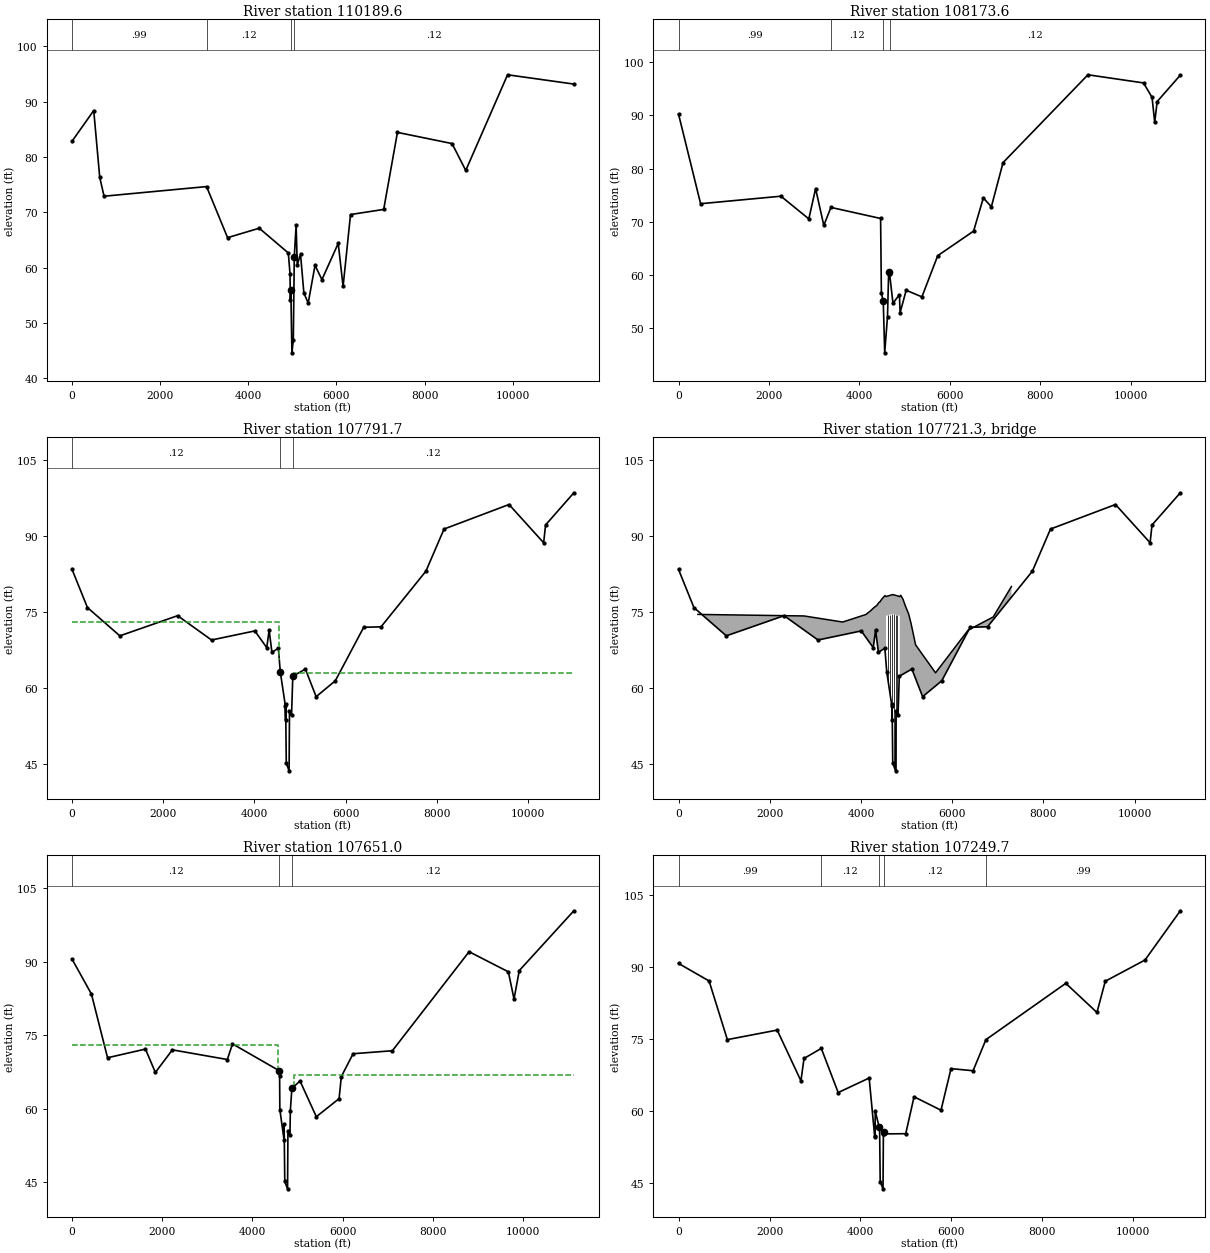
Type RM Length L Ch R = 1 ,110189.6,1337.33,2016.01,1634.35
BEGIN DESCRIPTION:
411v7
Bank Station offset =        10
Cross section trimmed on ROB due to lack of TIN data; considered limit of study.
block is beyond flow area
END DESCRIPTION:
XS GIS Cut Line= 6
     3198558.801    13984485.742     3193892.918    13985421.518
     3193269.067    13985928.397     3191019.081     13986239.11
     3188177.573    13986441.768     3187474.548    13986416.281
#Sta/Elev= 30
       0   82.83  491.62   88.37  627.88    76.3  725.63   72.89 3052.38   74.63
 3529.55    65.4 4248.38   67.11 4908.25   62.63 4946.55   58.85 4954.55   54.14
 4965.55   55.95 4989.55   44.59 5021.55   46.91 5043.55   61.93 5085.55   67.71
 5110.55   60.47 5185.21   62.42 5261.21   55.39  5359.7   53.59  5514.3    60.4
 5671.09   57.82  6040.9   64.37 6151.12   56.58 6319.76   69.58 7072.67    70.5
 7384.75   84.42 8624.27    82.4 8935.26   77.54 9884.42   94.8311388.89   93.15
#Mann= 4 ,-1 , 0
       0     .99       0 3052.38     .12       0 4965.55     .05       0
 5043.55     .12       0
#Block Obstruct= 2 , 0
       0                    7375       0    84.5
Bank Sta=4965.55,5043.55
XS Rating Curve= 0
Exp/Cntr=.3,.1

Type RM Length L Ch R = 1 ,108173.6,329.31,381.86,367.16
BEGIN DESCRIPTION:
411v8  XS 4/4
Bank Station offset =       441
END DESCRIPTION:
XS GIS Cut Line= 6
      3197895.96    13983991.861     3196462.585    13984590.809
     3193644.792    13984590.809     3191664.492    13985023.436
     3188080.973    13985605.024     3187020.903    13985599.236
#Sta/Elev= 30
       0   90.24  488.05   73.42 2264.11   74.83 2881.11   70.57 3030.97   76.26
 3212.41   69.34 3369.73   72.73 4468.57   70.65 4486.01   56.58  4527.5   55.11
 4558.99   45.42 4621.19   52.24 4646.71   60.65 4666.51   60.29 4742.31   54.74
 4884.71   56.33 4899.77   52.96 5034.39   57.17 5382.02   55.93 5731.99   63.66
 6525.54   68.28 6740.45   74.51 6918.05   72.85 7176.48   81.14 9054.05   97.63
10283.63    96.110472.07   93.3810530.47   88.6810584.16    92.611096.81   97.56
#Mann= 4 ,-1 , 0
       0     .99       0 3369.73     .12       0  4527.5     .05       0
 4666.51     .12       0
Bank Sta=4527.5,4646.71
XS Rating Curve= 0
Exp/Cntr=.5,.3

Type RM Length L Ch R = 1 ,107791.7,192.02,140.74,153.52
BEGIN DESCRIPTION:
411s1u:  XS 3/4
Bank Station offset =       241
END DESCRIPTION:
XS GIS Cut Line= 6
     3197763.084    13983933.567     3196210.875    13984562.841
     3195043.223    13984541.865     3192694.454    13984290.752
     3187974.824    13985147.054     3186976.472    13985154.927
#Sta/Elev= 30
       0   83.35  337.07   75.85 1047.73   70.28 2314.39   74.25 3058.17   69.46
 4007.59   71.25 4269.41   67.95 4320.99   71.41 4382.37   67.04 4523.82   67.84
 4565.65    63.2 4676.24   56.55 4681.36    53.7 4683.06    56.9 4697.05    45.2
 4759.03    43.7 4767.54   55.41 4812.42    54.6  4839.9   62.32 5116.28   63.74
 5352.06    58.3 5772.24   61.43 6394.59   71.96 6775.32   72.06 7759.14   83.02
 8156.23   91.31 9581.39   96.14 10340.3   88.6110382.44   92.1111002.93   98.45
#Mann= 3 ,-1 , 0
       0     .12       0 4565.65     .05       0  4839.9     .12       0
#XS Ineff= 2 , 0
       0    4545      73    4860       0      63
Permanent Ineff=
       F       F
Bank Sta=4565.65,4839.9
XS Rating Curve= 0
Exp/Cntr=.5,.3

Type RM Length L Ch R = 3 ,107721.3,,,
BEGIN DESCRIPTION:
FM 1485 (Huffman-Cleveland Road) 411s1
END DESCRIPTION:
Bridge Culvert--1,0,-1,-1, 0
Deck Dist Width WeirC Skew NumUp NumDn MinLoCord MaxHiCord MaxSubmerge Is_Ogee
47,46,2.6,0, 24, 26, , , .95, 0, 0,0,,
     425    2750    3600  4107.5 4210.25 4286.58 4349.85 4392.99 4418.39 4458.18
 4527.03    4549 4698.72    4851 4871.37 4921.44 4971.53 5046.68 5096.61 5198.17
    5635    6350    6900    7300
    74.5    74.2      73   74.48   75.21   75.85   76.28   76.85   76.99   77.54
   78.21   78.02   78.41   78.02   78.27    77.5   76.23   74.57    72.8   68.51
      63    71.4      74      80
                                                                                
           74.22   74.61   74.22
                                
     580    2776    3626  4126.5 4229.25 4305.58 4368.85 4411.99 4437.39 4477.18
 4546.03    4568 4717.72    4870 4890.37 4940.44 4990.53 5065.68 5115.61 5217.17
    5664    6297    6850    7380    8120    8760
    74.5    74.4      73   74.48   75.21   75.85   76.28   76.85   76.99   77.54
   78.21   78.02   78.41   78.02   78.27    77.5   76.23   74.57    72.8   68.51
      63    70.6      74      80      88      91
                                                                                
           74.22   74.61   74.22
                                                
Pier Skew, UpSta & Num, DnSta & Num=  ,4599, 3 ,4618, 3 , 2 , 2 , 0 ,0,
    1.35       2       2
   72.22   72.22      75
    1.35       2       2
   72.22   72.22      75
Pier Skew, UpSta & Num, DnSta & Num=  ,4639, 3 ,4658, 3 , 2 , 2 , 0 ,0,
    1.35       2       2
   72.22   72.22      75
    1.35       2       2
   72.22   72.22      75
Pier Skew, UpSta & Num, DnSta & Num=  ,4679, 3 ,4698, 3 , 2 , 2 , 0 ,0,
    1.35       2       2
   72.22   72.22      75
    1.35       2       2
   72.22   72.22      75
Pier Skew, UpSta & Num, DnSta & Num=  ,4719, 3 ,4738, 3 , 2 , 2 , 0 ,0,
    1.35       2       2
   72.22   72.22      75
    1.35       2       2
   72.22   72.22      75
Pier Skew, UpSta & Num, DnSta & Num=  ,4759, 3 ,4778, 3 , 2 , 2 , 0 ,0,
    1.35       2       2
   72.22   72.22      75
    1.35       2       2
   72.22   72.22      75
Pier Skew, UpSta & Num, DnSta & Num=  ,4799, 3 ,4818, 3 , 2 , 2 , 0 ,0,
    1.35       2       2
   72.22   72.22      75
    1.35       2       2
   72.22   72.22      75
Abutment Skew #Up #Dn= , 4 , 4
    4549    4559    4559  4596.5
   74.22   74.22   72.22   59.87
    4568    4578    4578  4615.5
   74.22   74.22   72.22   59.87
Abutment Skew #Up #Dn= , 4 , 4
  4801.5    4839    4839    4851
    54.6   72.22   74.22   74.22
  4820.5    4858    4858    4870
    54.6   72.22   74.22   74.22
BR Coef= 1 , 1 , 1 ,1.25, 0 ,,,.8,-1,2,0,
WSPro=,,,, 1 ,,,, 0 ,,,, 0 ,,,,-1 ,-1 ,-1 , 0 , 0 , 0 , 0 , 0
BC Design=,, 0 ,, 0 ,,,,,,

Type RM Length L Ch R = 1 ,107651.0,427.51,401.3,481.55
BEGIN DESCRIPTION:
Copy of 411s1u:  XS 2/4
Bank Station offset =       222
END DESCRIPTION:
XS GIS Cut Line= 6
     3197700.156     13983507.06     3196882.101    13984108.366
     3196078.029    13984388.043     3193779.103    13984272.358
     3192226.566    13984070.316     3186865.395    13984621.756
#Sta/Elev= 30
       0   90.55     429   83.44  786.95   70.44 1627.58   72.21  1846.6   67.44
 2224.07   72.05  3442.7   70.08 3557.29   73.27 4586.63   67.83 4601.69   66.79
 4607.16   59.87 4700.48    53.7 4702.18    56.9 4716.17    45.2 4778.15    43.7
 4786.66   55.41 4831.54    54.6 4839.76   59.58 4873.46   64.19    5055    65.7
 5415.61   58.41 5920.39   62.09 5970.73   66.61 6231.69   71.26 7101.94   71.87
 8803.44   92.07 9673.81   87.97 9799.46   82.43 9916.72   88.2311126.46  100.42
#Mann= 3 ,-1 , 0
       0     .12       0 4586.63     .05       0 4873.46     .12       0
#XS Ineff= 2 , 0
       0    4560      73    4915       0      67
Permanent Ineff=
       F       F
Bank Sta=4586.63,4873.46
XS Rating Curve= 0
Exp/Cntr=.5,.3

Type RM Length L Ch R = 1 ,107249.7,809.43,638.61,474.8
BEGIN DESCRIPTION:
Copy of 411s1u:  XS 1/4
Bank Station offset =       504
END DESCRIPTION:
XS GIS Cut Line= 6
     3197745.517    13983255.597     3196628.966    13983510.808
     3193779.103    13983872.358     3192226.566    13983670.316
      3191461.93    13983810.759     3186820.964    13984332.955
#Sta/Elev= 30
       0   90.71  671.54   87.05 1073.22   74.82 2168.66   76.81 2691.12   66.22
 2758.63   70.89 3138.65   72.99 3509.86   63.78 4191.01   66.81 4313.71   54.51
 4321.19   54.62 4324.74   59.87 4412.94   56.55 4419.76    56.9 4433.75    45.2
 4495.73    43.7 4503.73   55.09 4511.72    55.5 4527.55   55.16 4995.41    55.2
 5178.15    62.9 5770.51    60.1  5990.8   68.77 6476.02   68.33 6757.73   74.81
  8514.2   86.56 9199.26   80.48 9382.21      8710255.61   91.4211032.36  101.69
#Mann= 5 ,-1 , 0
       0     .99       0 3138.65     .12       0 4412.94     .05       0
 4527.55     .12       0 6757.73     .99       0
Bank Sta=4412.94,4511.72
XS Rating Curve= 0
Exp/Cntr=.3,.1

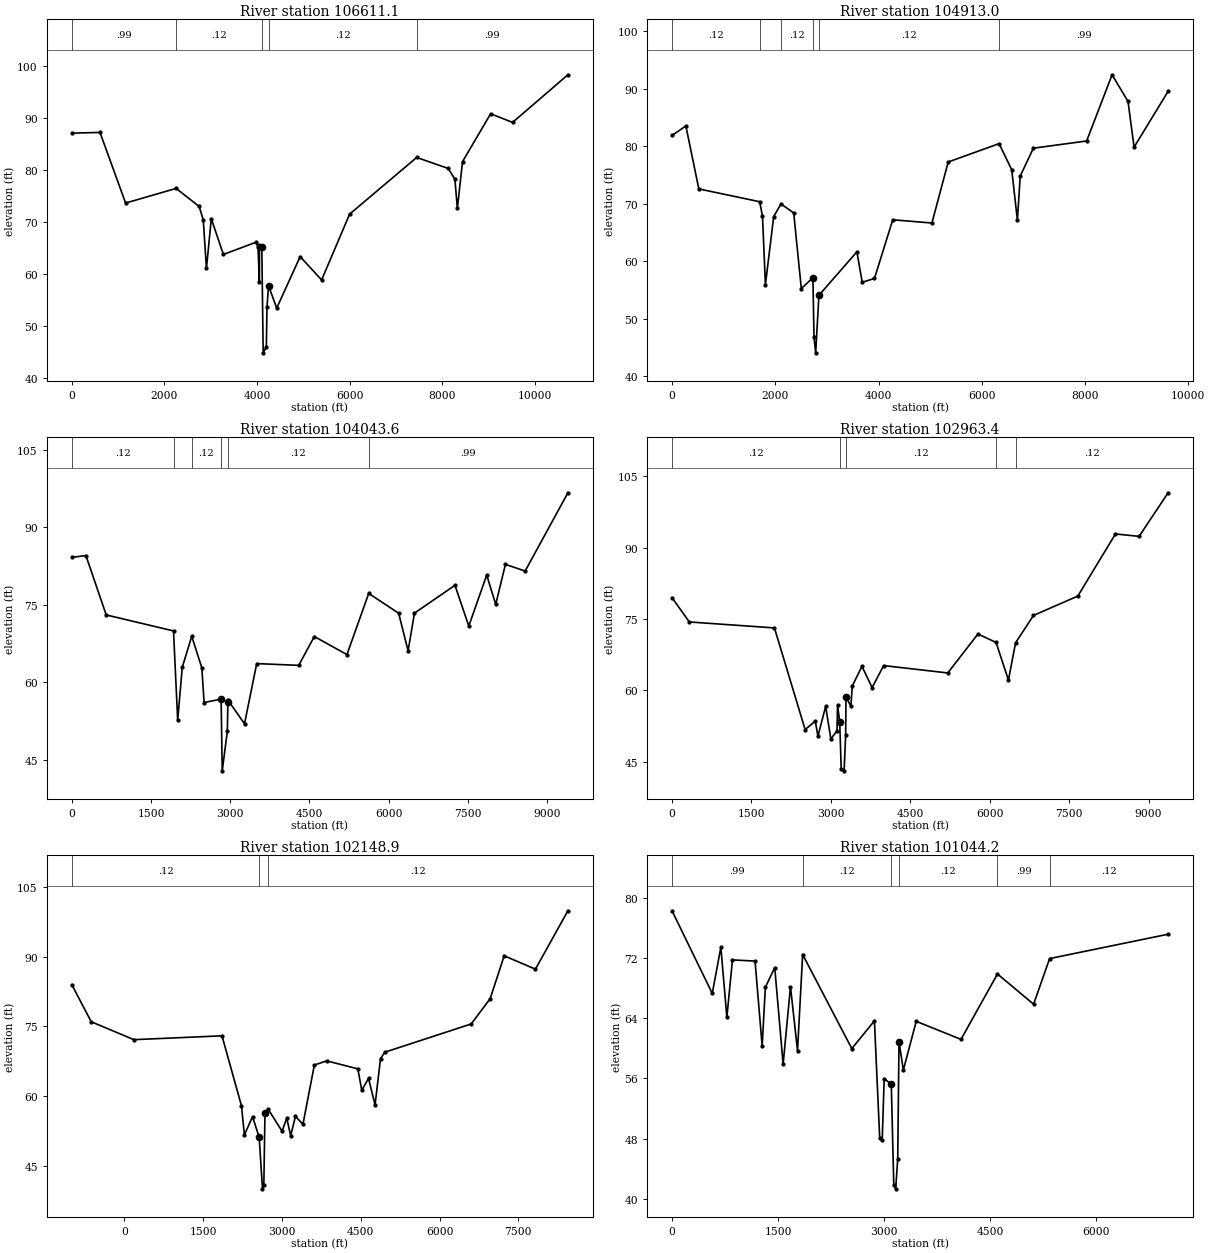
Type RM Length L Ch R = 1 ,106611.1,1364.17,1698.08,1222.21
BEGIN DESCRIPTION:
411v9
Bank Station offset =       868
END DESCRIPTION:
XS GIS Cut Line= 6
     3197364.544    13982954.697     3194066.216    13983035.962
     3193378.325    13983085.589     3193312.376    13983146.591
     3193134.315    13983323.004     3186754.317    13983288.828
#Sta/Elev= 30
       0   87.07  608.81   87.21 1161.64   73.61 2252.16   76.43 2750.16   72.95
 2838.28   70.36 2906.64   61.02 3011.67   70.59  3272.5   63.71 3977.09   66.07
 4020.41   65.08 4049.68   58.33 4051.77   65.45 4101.77   65.15 4131.77   44.77
 4199.77   45.87 4213.27   53.57 4248.27   57.67 4423.19   53.37 4929.94    63.3
 5392.92    58.8 5997.79   71.48 7445.07   82.39 8124.24   80.28 8270.08   78.21
 8323.27   72.61 8435.09   81.59 9041.39    90.8 9515.25   89.1410709.59   98.31
#Mann= 5 ,-1 , 0
       0     .99       0 2252.16     .12       0 4101.77     .05       0
 4248.27     .12       0 7445.07     .99       0
Bank Sta=4101.77,4248.27
XS Rating Curve= 0
Exp/Cntr=.3,.1

Type RM Length L Ch R = 1 ,104913.0,165.85,869.44,556.74
BEGIN DESCRIPTION:
411v10
Bank Station offset =      2217
END DESCRIPTION:
XS GIS Cut Line= 6
     3195746.359     13981249.48     3193885.441    13981674.833
     3193247.412    13981855.608     3193170.204    13981886.136
     3193233.064     13982148.51     3186554.378    13982311.348
#Sta/Elev= 30
       0    81.9  268.36   83.55  519.27   72.61 1697.34   70.38 1752.35   67.89
 1809.45   55.99 1969.88    67.8 2111.37   70.01 2357.56   68.42 2504.85   55.28
 2729.51   57.18 2750.51   46.81 2783.01   44.11 2846.01   54.11 3581.31   61.67
 3684.77   56.38 3921.96   57.04 4276.11   67.24 5034.92   66.68 5350.26   77.29
 6335.98   80.48 6580.92   75.93 6690.91   67.17 6745.68   74.85 7000.75   79.69
 8032.29   80.94 8524.85   92.45 8833.26   87.82 8951.33   79.87 9610.94   89.58
#Mann= 6 ,-1 , 0
       0     .12       0 1697.34     .99       0 2111.37     .12       0
 2729.51     .05       0 2846.01     .12       0 6335.98     .99       0
Bank Sta=2729.51,2846.01
XS Rating Curve= 0
Exp/Cntr=.3,.1

Type RM Length L Ch R = 1 ,104043.6,1019.47,1080.17,414.8
BEGIN DESCRIPTION:
411v11
Bank Station offset =      2151
END DESCRIPTION:
XS GIS Cut Line= 6
     3195778.261    13980983.635      3193353.75    13981653.565
     3192883.232    13981618.296     3190184.873    13981653.565
     3189195.927    13981759.904     3186487.584    13981885.986
#Sta/Elev= 30
       0   84.17  267.56   84.53  651.65   73.02 1926.11   69.92 2005.19    52.6
 2091.97   62.87 2271.18   68.89 2462.93   62.74 2505.33   56.04 2827.58   56.71
 2848.58   42.81 2945.58   50.51 2955.58   56.11 2957.58   56.51 3270.52   51.93
 3501.38   63.59 4297.03   63.25 4592.36   68.84 5209.81   65.34  5622.3   77.19
 6189.05   73.35 6368.03   66.06 6488.72   73.37 7255.45   78.77 7517.31   70.86
  7856.1   80.74  8027.3   75.06 8210.94   82.82 8583.99   81.52 9393.96   96.69
#Mann= 6 ,-1 , 0
       0     .12       0 1926.11     .99       0 2271.18     .12       0
 2827.58     .05       0 2957.58     .12       0  5622.3     .99       0
Bank Sta=2827.58,2955.58
XS Rating Curve= 0
Exp/Cntr=.3,.1

Type RM Length L Ch R = 1 ,102963.4,382.26,814.52,1011.57
BEGIN DESCRIPTION:
411v12
Bank Station offset =      1749
END DESCRIPTION:
XS GIS Cut Line= 6
     3195406.077    13980632.719     3194289.526    13980611.451
     3192513.679    13980781.592     3192439.242     13981249.48
     3189280.998    13981153.776     3186453.524    13981238.838
#Sta/Elev= 30
       0    79.5  327.08   74.39 1934.46   73.14 2513.93   51.77 2706.06   53.53
 2756.08   50.38 2902.36   56.65  3000.1   49.78  3116.7   51.52 3126.38   56.88
 3167.34   53.46 3195.86   43.41 3250.54   43.09 3279.92   50.61 3286.03   58.63
  3378.8   56.66 3404.57   60.92 3587.84   65.07 3778.93   60.59 3997.52   65.22
 5208.28   63.67 5778.23   71.85 6120.52   70.09  6354.4   62.17 6488.84      70
 6827.66   75.77 7664.68   79.83 8376.12    92.9 8821.87   92.38 9370.83  101.55
#Mann= 5 ,-1 , 0
       0     .12       0 3167.34     .05       0 3279.92     .12       0
 6120.52     .99       0 6488.84     .12       0
Bank Sta=3167.34,3286.03
XS Rating Curve= 0
Exp/Cntr=.3,.1

Type RM Length L Ch R = 1 ,102148.9,923.16,1104.62,928.19
BEGIN DESCRIPTION:
411v13
Bank Station offset =      2370
Extended XS on LOB
END DESCRIPTION:
XS GIS Cut Line= 6
 3195863.525721913980324.3338356      3192355.79    13980410.267
     3192149.575    13980329.133     3191843.748    13980303.071
     3189206.561    13980292.437     3186443.301    13980467.465
#Sta/Elev= 30
   -1000      84    -630      76  182.36   72.14 1859.14   72.97  2230.2   57.88
 2285.56   51.62 2440.64   55.55 2567.01    51.1 2630.01      40 2656.01    40.9
 2677.51    56.4 2736.01    57.2 3002.42   52.42 3092.56   55.22 3166.81   51.45
  3257.6   55.63  3400.1    53.9 3617.67   66.68 3853.24   67.57 4445.58   65.85
 4519.61   61.23 4648.49   63.81 4772.91   58.08 4876.97   68.07 4961.35   69.45
 6603.61   75.53 6964.14   80.97 7231.15   90.21 7825.63   87.33 8444.11   99.91
#Mann= 3 ,-1 , 0
   -1000     .12       0 2567.01     .05       0 2736.01     .12       0
Bank Sta=2567.01,2677.51
XS Rating Curve= 0
Exp/Cntr=.3,.1

Type RM Length L Ch R = 1 ,101044.2,646.03,914.27,257.19
BEGIN DESCRIPTION:
411v14
Bank Station offset =      1835
END DESCRIPTION:
XS GIS Cut Line= 6
     3194948.823    13979303.492      3194300.16    13979335.393
     3192024.523     13979633.14     3191705.509    13979388.562
     3190089.168    13979601.239     3188068.743     13979771.38
#Sta/Elev= 30
       0   78.31  569.68   67.31  691.31   73.47  776.12   64.13  855.38   71.77
 1175.04   71.62 1275.66   60.32 1321.01   68.13  1453.7   70.75 1572.39   57.89
 1676.41   68.22 1776.09   59.68 1848.81   72.49 2544.45   59.97  2864.4   63.66
 2939.43   48.03    2975   47.86 3002.69   55.99 3103.39   55.21 3138.39   41.81
 3165.39   41.31 3194.39   45.31 3212.39   60.91 3273.39   57.11 3456.15    63.6
 4089.76    61.2 4605.72    69.9 5117.09   65.88 5344.03   71.95 7021.25   75.19
#Mann= 6 ,-1 , 0
       0     .99       0 1848.81     .12       0 3103.39     .05       0
 3212.39     .12       0 4605.72     .99       0 5344.03     .12       0
Bank Sta=3103.39,3212.39
XS Rating Curve= 0
Exp/Cntr=.3,.1