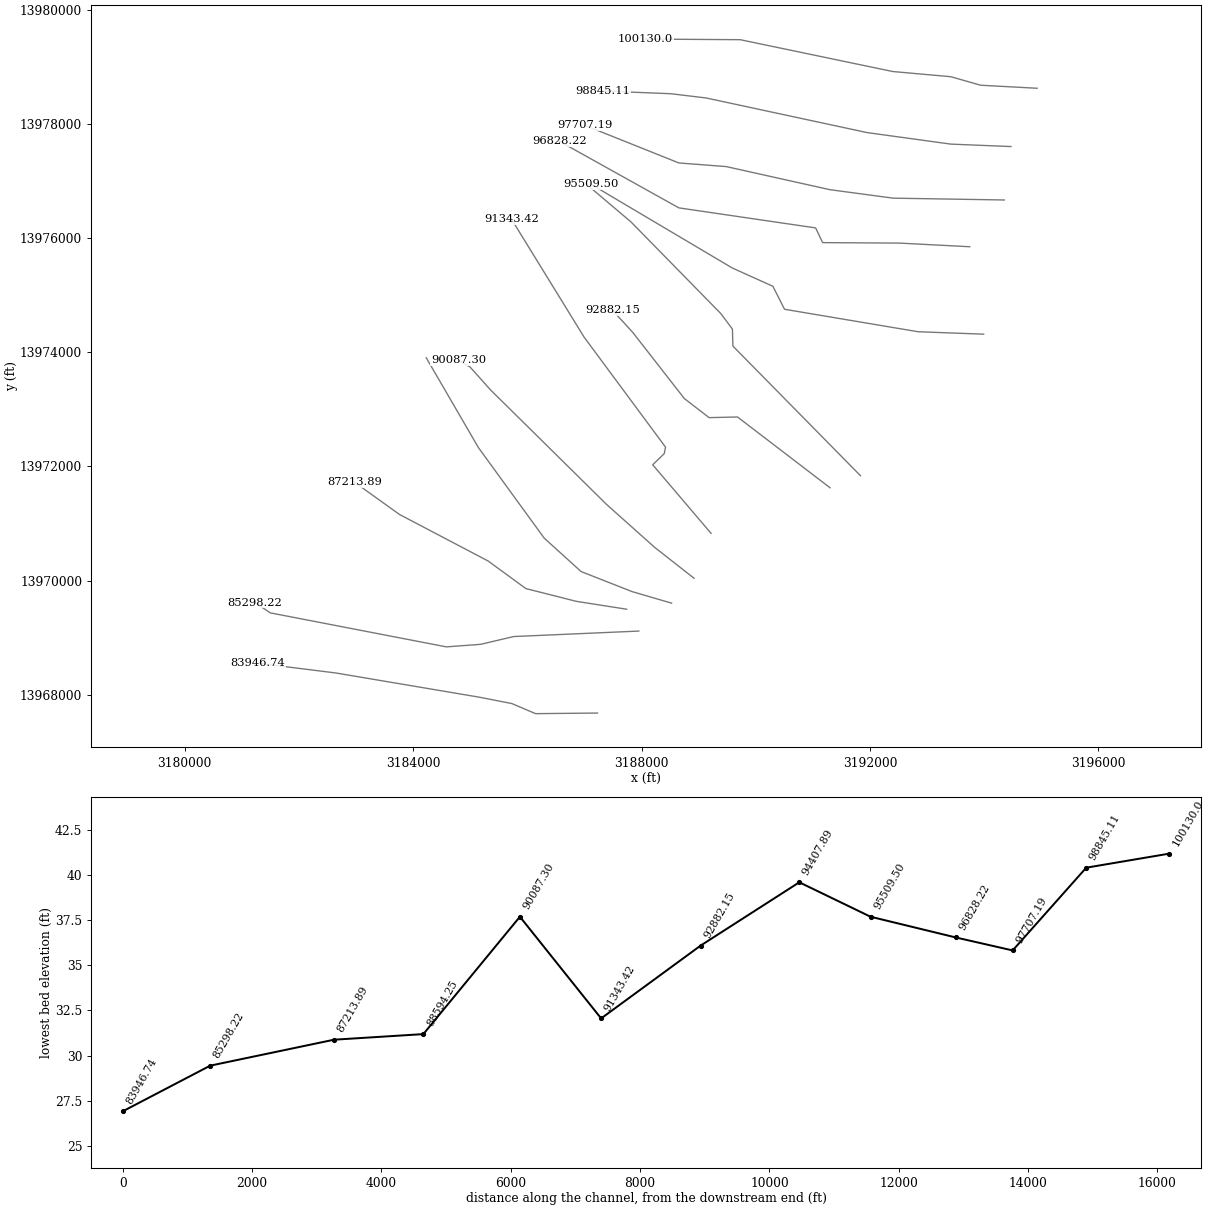
HEC-RAS study G103-80-00.prj: G103-80-00

--- G103-80-00.g03 (geometry) --- (continued)

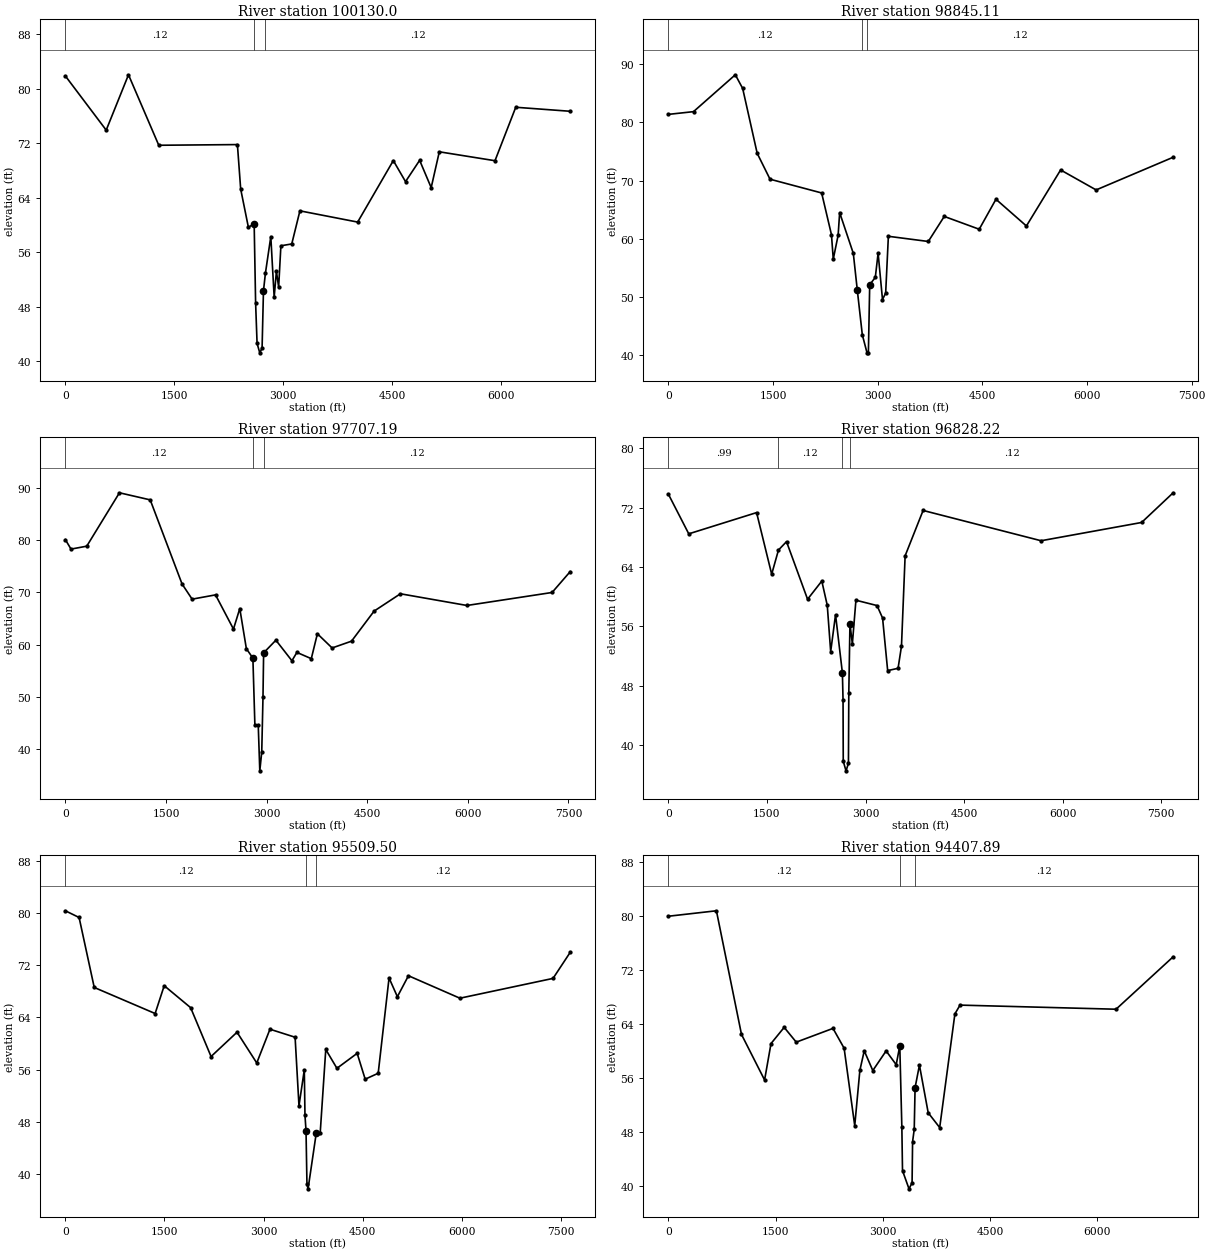
Type RM Length L Ch R = 1 ,100130.0,1169.69,1284.92,1149.31
BEGIN DESCRIPTION:
411v15
Bank Station offset =      2325
LOB block due to laterial streams.  Flow will not be conveyed downstream.
END DESCRIPTION:
XS GIS Cut Line= 6
     3194927.555    13978622.927      3193938.61    13978676.096
     3193417.553     13978824.97     3192399.738    13978916.055
     3189727.618    13979473.633     3188068.743    13979484.267
#Sta/Elev= 30
       0   81.86  562.25    73.9  868.93   82.03 1285.77   71.68 2367.84   71.78
 2412.86   65.25 2518.79   59.64 2598.42   60.14 2618.42    48.5 2638.42    42.6
 2675.42    41.2 2707.42    41.9 2726.42    50.3 2753.42    52.9 2827.45   58.27
 2873.72   49.38 2904.56   53.18 2935.41   50.86 2966.26   56.92 3115.77   57.19
 3227.96   62.05 4022.75    60.4 4513.28   69.43 4681.46   66.34 4875.65   69.47
 5034.49   65.46 5146.31   70.72 5912.53   69.41  6198.2   77.26 6947.63   76.67
#Mann= 3 ,-1 , 0
       0     .12       0 2598.42     .05       0 2753.42     .12       0
Bank Sta=2598.42,2726.42
XS Rating Curve= 0
Exp/Cntr=.3,.1

Type RM Length L Ch R = 1 ,98845.11,1117.14,1137.92,1122.36
BEGIN DESCRIPTION:
411v16
Bank Station offset =      2152
END DESCRIPTION:
XS GIS Cut Line= 6
     3194470.301    13977602.081     3193417.553    13977644.616
     3191950.086    13977846.659     3189132.125    13978452.786
     3188515.363    13978527.223 3187321.020294813978574.9976067
#Sta/Elev= 30
       0   81.36  361.06   81.83   960.4   88.16 1065.58   85.82 1273.61   74.68
 1457.73   70.23 2197.38   67.87 2338.03   60.71    2364   56.51 2433.78   60.62
 2455.44    64.5 2651.19    57.5 2707.64   51.27 2780.23   43.52 2847.73   40.42
 2867.23   40.42 2886.23   52.12  2966.4   53.37 3006.62   57.53  3069.5   49.57
 3114.99   50.69 3153.64   60.43 3725.81   59.54 3954.62   63.84 4455.57   61.64
 4695.42   66.79 5131.95    62.2 5622.15   71.82 6131.13   68.39    7235      74
#Mann= 3 ,-1 , 0
       0     .12       0 2780.23     .05       0 2847.73     .12       0
Bank Sta=2707.64,2886.23
XS Rating Curve= 0
Exp/Cntr=.3,.1

Type RM Length L Ch R = 1 ,97707.19,903.9,878.97,760.13
BEGIN DESCRIPTION:
411v17
Bank Station offset =      2101
END DESCRIPTION:
XS GIS Cut Line= 6
     3194353.329    13976666.305     3192407.341    13976698.206
     3191301.608    13976846.157     3189483.041    13977251.165
     3188653.603    13977314.968 3187011.561935213977971.7782493
#Sta/Elev= 30
       0   80.13   84.48   78.31  319.04   78.87  806.36    89.1 1265.11   87.74
 1739.77   71.63 1889.81   68.72 2238.72   69.54 2506.25   62.99 2600.48   66.92
  2698.5   59.23 2795.71   57.43 2825.71   44.53 2875.71   44.53 2898.71   35.83
 2927.71   39.43 2946.21   49.93 2955.71   58.43 3138.76   60.86 3377.66   56.92
 3451.78   58.52 3666.35   57.32 3757.18   62.09 3976.79   59.37  4265.9   60.67
 4602.53   66.43 4995.15   69.75 5986.53   67.51    7256      70    7526      74
#Mann= 3 ,-1 , 0
       0     .12       0 2795.71     .05       0 2955.71     .12       0
Bank Sta=2795.71,2955.71
XS Rating Curve= 0
Exp/Cntr=.3,.1

Type RM Length L Ch R = 1 ,96828.22,1507.54,1318.72,1097.41
BEGIN DESCRIPTION:
411v18
Bank Station offset =      2297
ROB flow will be conveyed for 500yr flood
END DESCRIPTION:
XS GIS Cut Line= 6
     3193747.202    13975847.501     3192513.679    13975911.304
     3191171.213    13975919.609     3191049.103    13976177.186
     3188653.603    13976528.065 3186562.063069113977693.9193696
#Sta/Elev= 30
       0   73.83  311.12   68.47 1343.01   71.33 1572.48   63.03 1675.72   66.29
  1798.2   67.42  2118.5   59.66 2334.95   62.11 2418.08   58.84 2470.07   52.61
 2543.98   57.58 2648.22   49.75 2658.22   46.05 2661.22   37.85 2703.22   36.55
 2740.22   37.55 2745.72   47.05 2763.22   56.35 2799.72   53.65 2854.03   59.53
 3175.07   58.81 3259.44   57.13 3336.87   50.05 3495.28   50.36 3547.03   53.34
  3602.5   65.51 3876.04   71.62  5670.7   67.54    7200      70    7680      74
#Mann= 4 ,-1 , 0
       0     .99       0 1675.72     .12       0 2648.22     .05       0
 2763.22     .12       0
Bank Sta=2648.22,2763.22
XS Rating Curve= 0
Exp/Cntr=.3,.1

Type RM Length L Ch R = 1 ,95509.50,1428.55,1101.61,867.19
BEGIN DESCRIPTION:
411v19
Bank Station offset =      1326
ROB flow will be conveyed for 500yr flood
END DESCRIPTION:
XS GIS Cut Line= 6
     3193991.779    13974316.231     3192843.327    13974358.766
     3190503.887    13974752.218      3190300.42    13975154.866
     3189589.379    13975475.317 3187113.566549813976942.3963287
#Sta/Elev= 30
       0   80.38  208.14   79.35   437.3   68.61 1358.79   64.61 1496.35   68.88
  1896.1   65.51 2205.33   58.01 2598.36   61.74 2897.01   57.02  3096.9    62.2
 3477.32   60.97 3536.01   50.45 3616.73   55.96  3626.7      49  3642.7    46.6
  3656.7    38.4  3673.7    37.7  3796.7    46.2  3856.7    46.2 3941.45   59.09
 4110.46    56.2 4416.66    58.5 4538.02   54.53 4734.91   55.44 4899.33   70.07
 5025.36   67.19 5192.89   70.41 5971.65   66.96    7381      70    7641      74
#Mann= 3 ,-1 , 0
       0     .12       0  3642.7     .05       0  3796.7     .12       0
Bank Sta=3642.7,3796.7
XS Rating Curve= 0
Exp/Cntr=.3,.1

Type RM Length L Ch R = 1 ,94407.89,829.57,1525.75,1548.96
BEGIN DESCRIPTION:
411v20
Bank Station offset =      1632
ROB flow will be conveyed for 500yr flood
END DESCRIPTION:
XS GIS Cut Line= 6
     3191833.114    13971838.551      3189600.06    13974107.487
     3189591.644    13974404.846     3189387.336    13974677.781
     3187813.531    13976283.487 3187065.164138313976916.7234134
#Sta/Elev= 30
       0   80.01  672.96   80.82 1024.09   62.49  1347.2   55.74 1436.84   61.14
 1621.16   63.54 1790.08   61.35 2304.24   63.39 2459.89   60.45 2608.53   48.97
 2680.15   57.16  2741.5   60.07 2861.31   57.14 3047.53   60.05 3188.88   58.01
 3238.88   60.81 3267.88   48.71 3276.88   42.31 3367.88   39.61 3410.88   40.51
 3417.88   46.61 3440.88   48.41 3452.88   54.61 3513.81   57.94 3636.44   50.88
 3797.25   48.69 4010.01   65.54 4081.85   66.84 6264.76   66.23    7064      74
#Mann= 3 ,-1 , 0
       0     .12       0 3238.88     .05       0 3452.88     .12       0
Bank Sta=3238.88,3452.88
XS Rating Curve= 0
Exp/Cntr=.3,.1

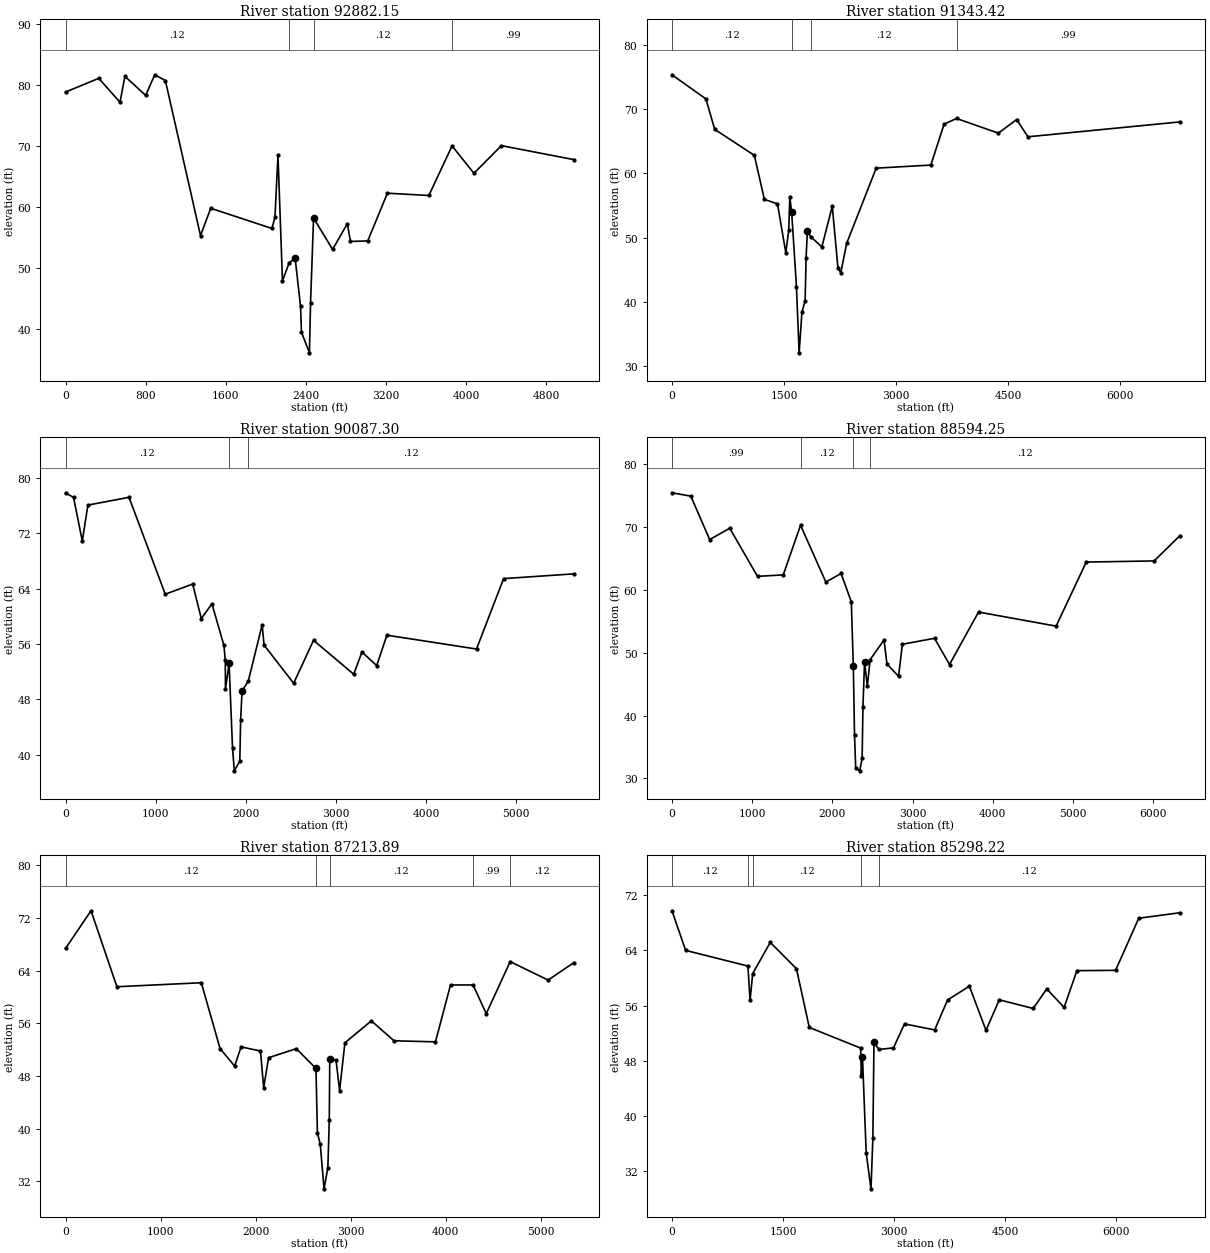
Type RM Length L Ch R = 1 ,92882.15,1751.77,1538.72,830.92
BEGIN DESCRIPTION:
411v21
Bank Station offset =      2563
block on ROB to close cross section
END DESCRIPTION:
XS GIS Cut Line= 6
     3191301.423    13971625.875     3189680.506    13972865.869
     3189183.064    13972854.432     3188749.307    13973189.046
     3187845.433    13974348.132     3187494.517     13974730.95
#Sta/Elev= 30
       0   78.83  332.86   81.08  544.33   77.16  593.84    81.4  801.15   78.28
   891.2   81.66  997.78   80.71 1348.81    55.3 1450.67   59.79 2062.21   56.48
 2092.57    58.3 2122.57   68.54 2167.57   47.86 2233.23   50.81 2294.14    51.6
 2348.14    43.7 2357.14    39.5 2437.14    36.1 2448.14    44.3 2478.14    58.2
 2668.25   53.04 2815.53   57.25 2847.03   54.35 3019.53   54.44 3215.77   62.26
 3629.85   61.88 3861.86   70.01 4080.25   65.52 4354.76   70.05 5075.53   67.77
#Mann= 4 ,-1 , 0
       0     .12       0 2233.23     .05       0 2478.14     .12       0
 3861.86     .99       0
#Block Obstruct= 2 , 0
       0                 4354.76       0   70.05
Bank Sta=2294.14,2478.14
XS Rating Curve= 0
Exp/Cntr=.3,.1

Type RM Length L Ch R = 1 ,91343.42,977.67,1256.12,1651.13
BEGIN DESCRIPTION:
411v22
Bank Station offset =      3298
END DESCRIPTION:
XS GIS Cut Line= 6
     3189217.195    13970828.339     3188195.201    13972028.836
     3188397.901    13972224.297     3188419.659    13972338.341
     3186994.727    13974263.062 3185722.625574113976330.2258825
#Sta/Elev= 30
       0   75.33  453.93   71.58  571.85   66.84 1102.21   62.79 1237.22   55.94
 1412.38   55.24 1523.75   47.64 1563.13    51.2 1577.03   56.26 1602.03   53.96
 1666.03   42.36 1702.03   32.06 1740.03   38.46 1782.53   40.16 1795.03   46.86
 1812.03   50.96 1858.16   50.12 2006.19   48.55 2145.79   54.87 2220.99   45.31
 2259.37   44.49 2337.64   49.08 2733.26    60.8 3465.16   61.28 3642.42   67.65
  3809.3   68.53  4368.2   66.25 4613.08   68.36 4764.63   65.68    6800      68
#Mann= 4 ,-1 , 0
       0     .12       0 1602.03     .04       0 1858.16     .12       0
  3809.3     .99       0
Bank Sta=1602.03,1812.03
XS Rating Curve= 0
Exp/Cntr=.3,.1

Type RM Length L Ch R = 1 ,90087.30,1219.92,1493.05,1029.89
BEGIN DESCRIPTION:
411v23
Bank Station offset =      3127
block on ROB to close cross section
END DESCRIPTION:
XS GIS Cut Line= 6
     3188919.448    13970041.436      3188228.25    13970583.761
     3187387.646    13971334.193     3185357.119     13973337.92
     3184995.569    13973742.005     3184793.527    13973858.977
#Sta/Elev= 30
       0   77.81    89.4   77.13  186.33   70.85   248.2   76.03  704.54   77.16
 1106.51   63.18 1410.66   64.64 1506.21   59.67 1624.36   61.79 1757.17   55.79
  1771.8   53.73 1774.66    49.5 1814.66    53.2 1852.66      41 1872.66    37.7
 1933.66    39.1 1942.66    45.1 1958.66    49.2 2028.82   50.71  2181.7   58.77
  2202.5   55.84 2530.96   50.33 2751.26   56.53 3197.49   51.63 3288.33   54.84
 3452.07   52.88 3565.17   57.27 4559.16   55.27 4859.83   65.43  5635.6   66.11
#Mann= 3 ,-1 , 0
       0     .12       0 1814.66     .04       0 2028.82     .12       0
#Block Obstruct= 2 , 0
       0                 5296.06       0   67.79
Bank Sta=1814.66,1958.66
XS Rating Curve= 0
Exp/Cntr=.3,.1

Type RM Length L Ch R = 1 ,88594.25,923.1,1380.36,1545.86
BEGIN DESCRIPTION:
411v24
Bank Station offset =      2660
END DESCRIPTION:
XS GIS Cut Line= 6
     3188525.997     13969605.45     3187834.799    13969807.492
     3186941.558    13970158.408     3186295.583     13970743.83
     3185144.443    13972327.707     3184229.935    13973901.512
#Sta/Elev= 30
       0   75.46  235.11   74.92  469.85   68.01  720.12   69.81 1066.49   62.15
 1387.34   62.39 1602.69   70.29 1917.89   61.25  2108.4   62.61 2235.47   58.09
 2260.47   47.89 2275.47   36.89 2290.47   31.59 2340.47   31.19 2370.47   33.19
 2380.47   41.39 2400.47   48.49 2435.47   44.69 2470.47   48.89 2642.78   52.03
 2679.88    48.2 2824.44   46.24 2871.65   51.34 3272.62   52.29 3459.64   48.12
 3821.45   56.47 4788.31   54.23    5164   64.43 6009.96   64.61 6332.79   68.65
#Mann= 4 ,-1 , 0
       0     .99       0 1602.69     .12       0 2260.47     .04       0
 2470.47     .12       0
Bank Sta=2260.47,2400.47
XS Rating Curve= 0
Exp/Cntr=.3,.1

Type RM Length L Ch R = 1 ,87213.89,837.62,1915.68,1942.11
BEGIN DESCRIPTION:
411v25
Bank Station offset =      2281
END DESCRIPTION:
XS GIS Cut Line= 6
     3187739.094    13969499.112     3186856.488    13969637.351
     3185973.881    13969860.661     3185312.815    13970343.765
     3183762.047    13971157.987     3182975.144    13971721.579
#Sta/Elev= 30
       0   67.39  268.47   73.12  540.65   61.58 1428.34   62.19 1625.45   52.19
 1778.97   49.53 1846.33   52.44 2050.24   51.82 2084.24   46.26 2135.99    50.8
 2427.31   52.18 2634.15   49.18 2649.15   39.38 2679.15   37.68 2719.15   30.88
 2759.15   34.08 2774.15   41.28 2779.15   50.58 2845.37   50.42 2882.55   45.81
 2938.36   53.06 3216.24    56.4 3455.05   53.37 3890.95   53.21 4049.07   61.85
 4286.57   61.85 4425.04   57.49 4676.61    65.4 5075.58   62.59 5343.09   65.21
#Mann= 5 ,-1 , 0
       0     .12       0 2634.15     .04       0 2779.15     .12       0
 4286.57     .99       0 4676.61     .12       0
#Block Obstruct= 2 , 0
       0                    4700       0      66
Bank Sta=2634.15,2779.15
XS Rating Curve= 0
Exp/Cntr=.3,.1

Type RM Length L Ch R = 1 ,85298.22,1479.93,1351.48,850.3
BEGIN DESCRIPTION:
411v26
Bank Station offset =      2313
END DESCRIPTION:
XS GIS Cut Line= 6
     3187951.771    13969116.294     3185761.204     13969020.59
     3185180.316    13968884.081     3184580.851    13968839.815
     3181497.043    13969435.309     3181231.198    13969616.084
#Sta/Elev= 30
       0   69.74  184.74      64 1024.88   61.73 1054.47   56.77 1089.93   60.64
 1327.34   65.16  1680.5   61.35 1854.05   52.83  2547.3   49.84  2557.3   45.74
  2572.3   48.54  2622.3   34.64  2687.3   29.44  2712.3   36.74  2727.3   50.74
  2792.3   49.64 2990.86   49.87 3139.55   53.35 3546.72   52.47 3721.52   56.82
 4015.73   58.81 4240.03   52.41 4419.14   56.84 4876.99   55.58 5059.77   58.42
 5294.55   55.73 5467.45   61.06 5989.63   61.11 6302.25   68.66 6859.47   69.46
#Mann= 5 ,-1 , 0
       0     .12       0 1024.88     .99       0 1089.93     .12       0
  2547.3     .04       0  2792.3     .12       0
Bank Sta=2572.3,2727.3
XS Rating Curve= 0
Exp/Cntr=.3,.1

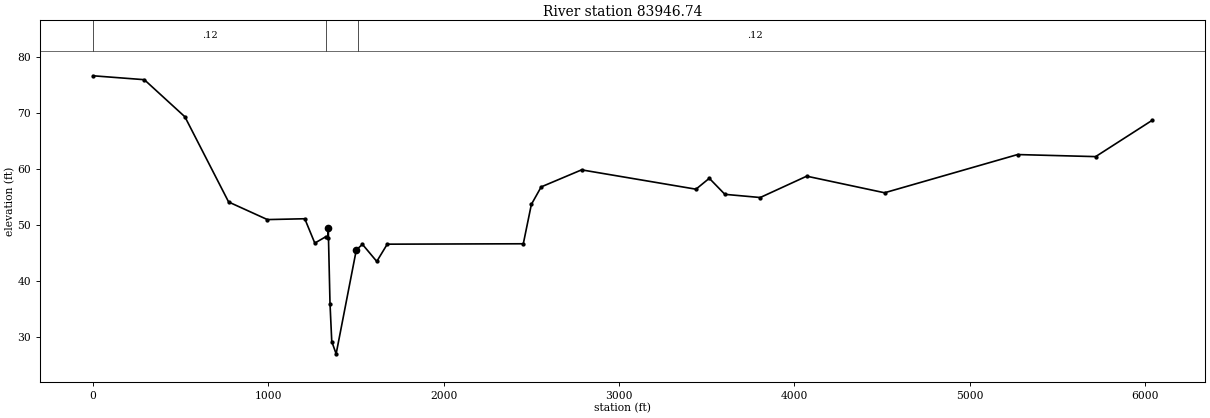
Type RM Length L Ch R = 1 ,83946.74,916.6,1363.39,1037.34
BEGIN DESCRIPTION:
411v27
Bank Station offset =      3614
END DESCRIPTION:
XS GIS Cut Line= 6
     3187228.671    13967680.729     3186144.022    13967670.095
     3185727.837    13967847.109     3185165.711    13967957.208
     3182645.496    13968382.561     3181284.367    13968552.702
#Sta/Elev= 30
       0   76.68  292.26   75.98  523.75   69.34  773.18   54.09  994.34   50.94
 1207.56   51.09 1264.74   46.73  1329.4   47.91 1340.74   47.63 1341.48   49.41
 1351.48   35.91 1361.48   29.11 1386.48   26.91 1501.48   45.51 1536.48   46.51
 1618.24   43.45 1677.99   46.54 2454.05   46.61 2500.08   53.66 2555.98   56.79
 2786.49   59.84 3438.92   56.38 3514.98   58.33 3603.85   55.46 3805.47   54.89
 4070.52   58.71 4514.67   55.74 5273.54   62.58 5718.63   62.21 6042.71   68.74
#Mann= 3 ,-1 , 0
       0     .12       0  1329.4     .04       0 1510.68     .12       0
Bank Sta=1341.48,1501.48
XS Rating Curve= 0
Exp/Cntr=.3,.1