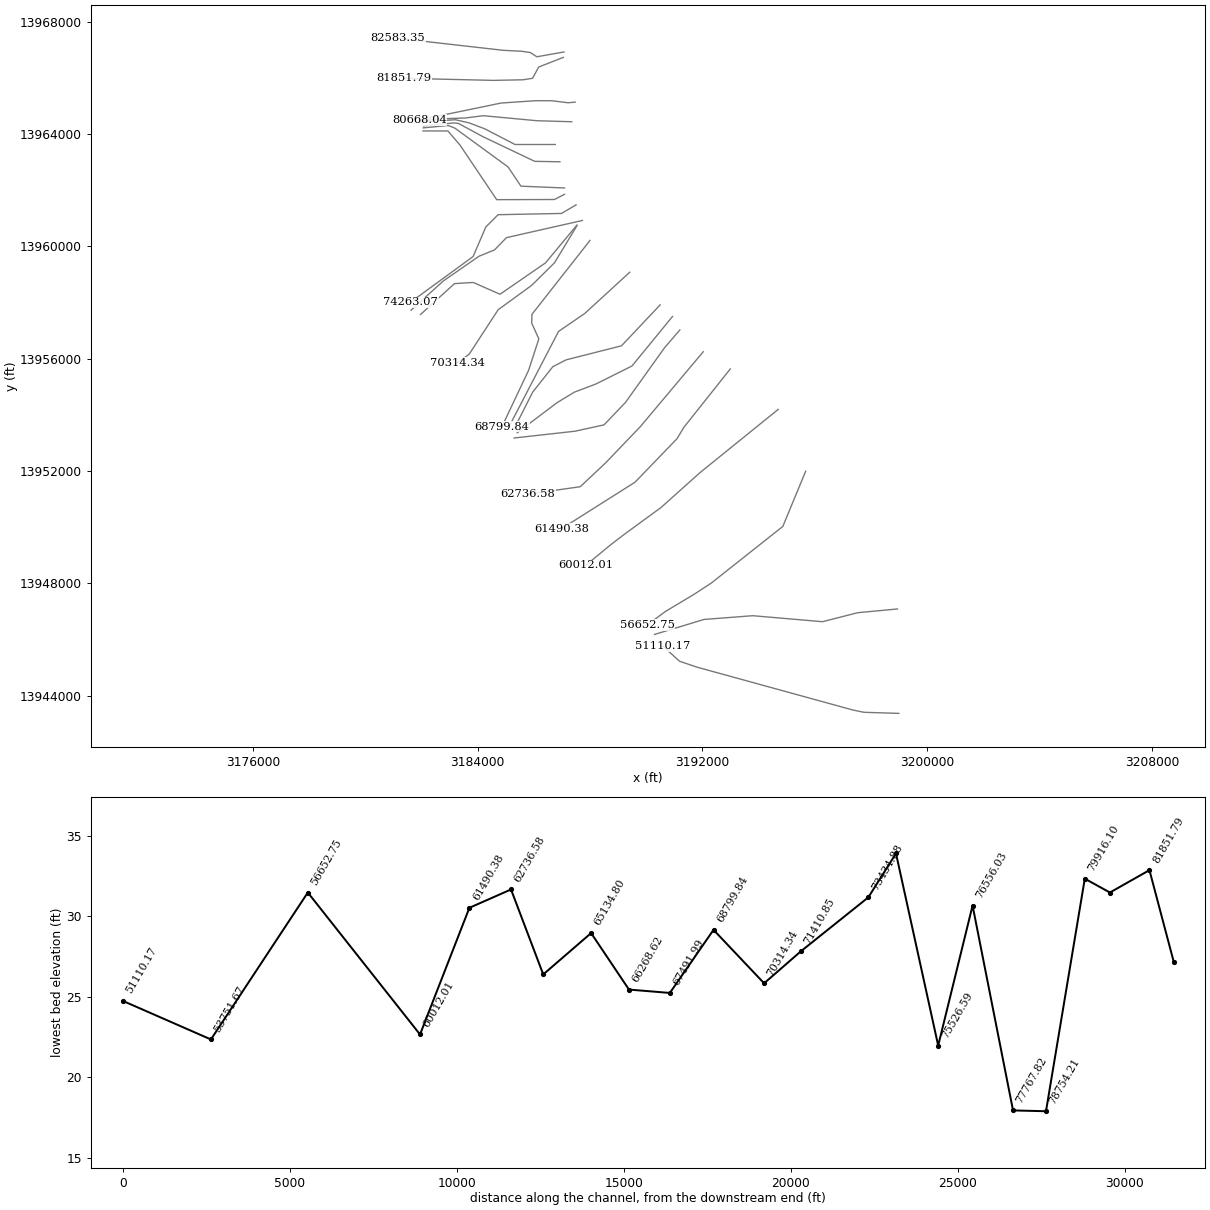
HEC-RAS study G103-80-00.prj: G103-80-00

--- G103-80-00.g03 (geometry) --- (continued)

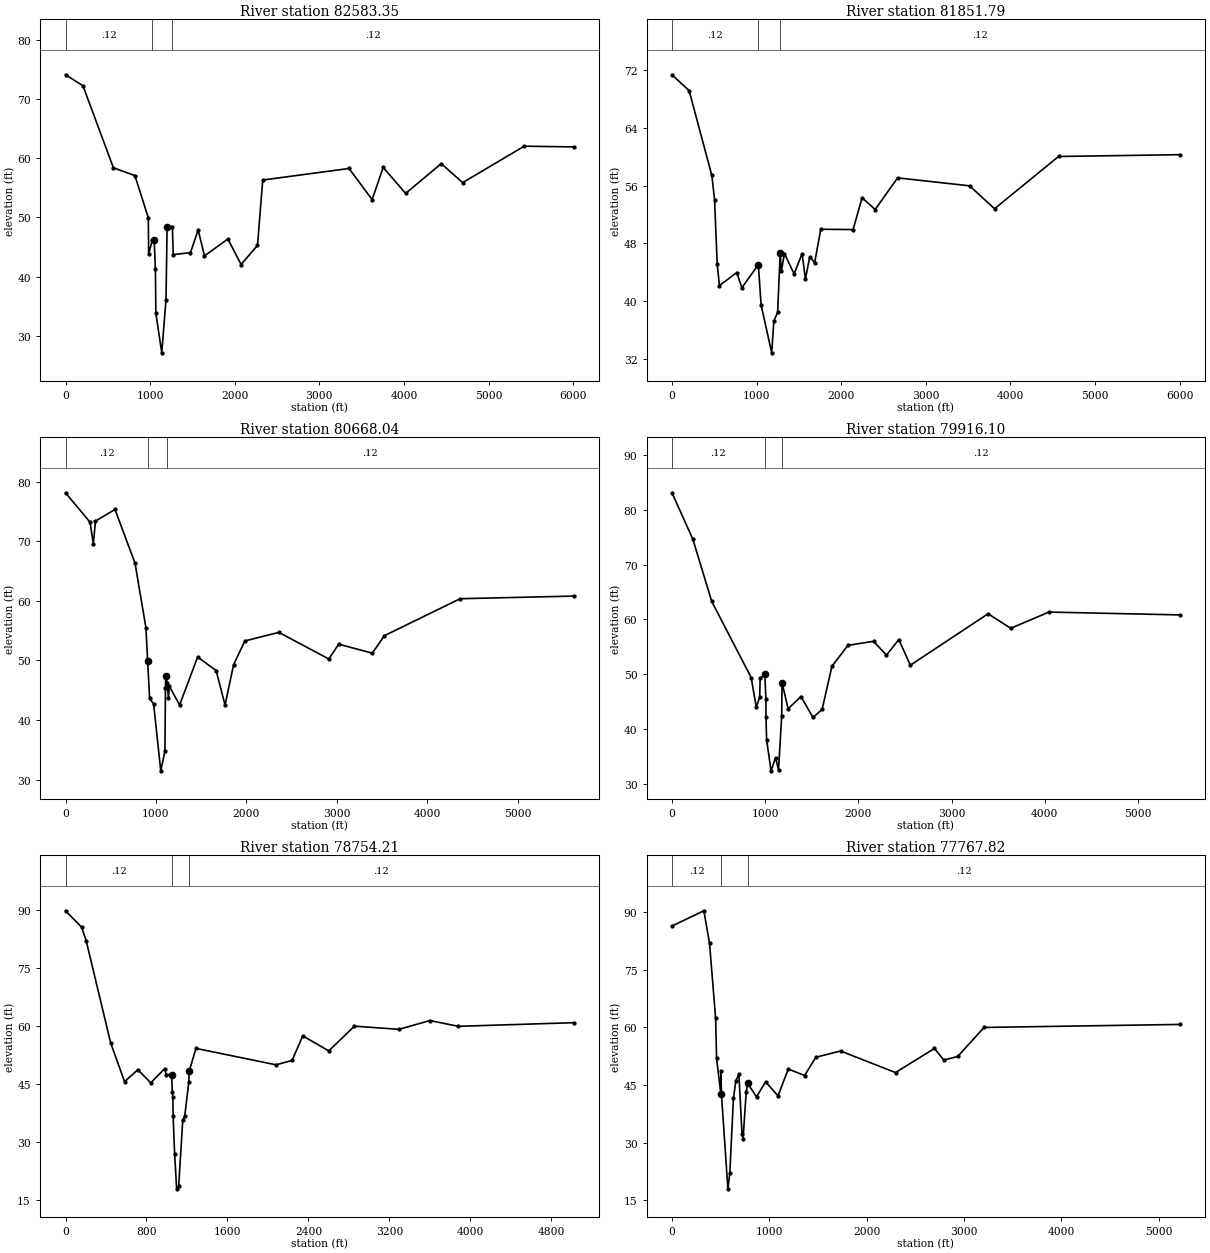
Type RM Length L Ch R = 1 ,82583.35,349.94,731.56,1063.17
BEGIN DESCRIPTION:
411v28
Bank Station offset =      3862
ROB block at edge of watershed
END DESCRIPTION:
XS GIS Cut Line= 6
     3187068.446    13966916.486     3186104.871    13966745.258
     3185873.263    13966895.209     3185568.909    13966941.068
     3184905.179    13966975.484      3181152.09    13967401.781
#Sta/Elev= 30
       0   74.05  206.02    72.2  566.31   58.35  820.05   57.04  978.67   49.93
  982.73   43.83 1027.73   46.23 1047.73   46.13 1062.73   41.23 1067.73   33.83
 1137.73   27.13 1187.73   36.13 1200.73   48.43 1262.73   48.43 1273.48    43.7
 1477.24   44.04 1567.52   47.88 1642.62   43.49 1919.29   46.34 2075.43   42.03
 2269.04   45.27 2331.02   56.29 3350.88   58.24 3623.86   52.98 3754.47   58.42
  4019.9   54.03 4440.53   59.06 4693.58   55.85 5421.13      62 6004.35   61.88
#Mann= 3 ,-1 , 0
       0     .12       0 1027.73     .04       0 1262.73     .12       0
#Block Obstruct= 2 , 0
       0                    5835       0      65
Bank Sta=1047.73,1200.73
XS Rating Curve= 0
Exp/Cntr=.3,.1

Type RM Length L Ch R = 1 ,81851.79,1318.04,1183.75,801.19
BEGIN DESCRIPTION:
411v29
Bank Station offset =      3821
ROB block at edge of watershed
END DESCRIPTION:
XS GIS Cut Line= 6
     3187047.896    13966723.685      3186170.22    13966381.301
     3185952.613    13965979.318     3185612.331    13965926.149
     3184559.583    13965904.881     3181358.804    13965979.318
#Sta/Elev= 30
       0   71.35  202.53   69.16  470.83   57.42  503.43   54.08  534.14   45.19
  560.73   42.17   765.6   43.98  825.76   41.87 1020.58   45.06 1053.58   39.46
 1178.58   32.86 1203.58   37.26 1248.58   38.46 1278.58   46.71 1293.58   44.21
 1328.58   46.61 1442.85   43.79    1538   46.58 1576.72   43.08 1628.37   46.16
 1685.76   45.33 1758.69   49.97 2139.91   49.92 2246.99   54.33 2400.76    52.7
 2666.19   57.08 3516.55   55.98 3811.81   52.81 4568.13   60.04  6003.4   60.29
#Mann= 3 ,-1 , 0
       0     .12       0 1020.58     .04       0 1278.58     .12       0
#Block Obstruct= 2 , 0
       0                    5680       0      65
Bank Sta=1020.58,1278.58
XS Rating Curve= 0
Exp/Cntr=.3,.1

Type RM Length L Ch R = 1 ,80668.04,726.01,751.94,567.57
BEGIN DESCRIPTION:
411v30
Bank Station offset =      3946
ROB block at edge of watershed
XS extended on ROB
END DESCRIPTION:
XS GIS Cut Line= 6
      3187468.98    13965129.451     3187212.663    13965108.945
     3186633.434    13965179.874     3186069.581    13965181.653
     3184834.042    13965098.693 3181920.903603913964496.5576137
#Sta/Elev= 30
       0   78.14  271.15    73.2  307.59   69.62  331.72   73.39  547.19   75.34
  769.04   66.32   889.6   55.47   908.1   49.97   930.1   43.67   974.6   42.67
  1053.6   31.47  1099.6   34.77  1105.6   45.37  1108.6   47.47  1123.6   46.27
  1138.6   43.67  1148.6   45.67    1262   42.52 1461.16   50.57 1665.68   48.31
 1764.57   42.51 1859.32   49.29 1983.69   53.27 2359.68   54.71 2912.47   50.24
 3021.26   52.73 3393.23   51.22 3527.46   54.16 4364.92   60.36    5619    60.8
#Mann= 3 ,-1 , 0
       0     .12       0   908.1     .04       0  1123.6     .12       0
#Block Obstruct= 2 , 0
       0                    5614       0      65
Bank Sta=908.1,1108.6
XS Rating Curve= 0
Exp/Cntr=.3,.1

Type RM Length L Ch R = 1 ,79916.10,1045.34,1161.89,707.14
BEGIN DESCRIPTION:
411v31
Bank Station offset =      3937
ROB block at edge of watershed
XS extended on ROB
END DESCRIPTION:
XS GIS Cut Line= 6
     3187345.948    13964432.269     3186100.725    13964468.831
     3184198.376    13964647.575     3183552.457    13964565.554
     3182639.969    13964534.796        3181929.       13964460.
#Sta/Elev= 30
       0    83.1  224.53    74.6  426.79   63.25   849.8   49.36  904.76   43.91
  941.46   45.85  946.16   49.23  996.16   49.93 1008.16   45.43 1008.66   42.23
 1015.16   38.03 1063.16   32.33 1111.16   34.73 1143.16   32.53 1177.16   42.33
 1181.16   48.43 1246.11   43.66 1383.78   45.89 1513.72   42.07  1610.9   43.53
 1716.42   51.43 1888.64   55.25 2162.82   55.98  2301.5   53.45 2434.38   56.31
 2557.13   51.61 3391.93   61.01  3634.9   58.36  4044.6   61.32    5451    60.8
#Mann= 3 ,-1 , 0
       0     .12       0  996.16     .04       0 1181.16     .12       0
#Block Obstruct= 2 , 0
       0                    5446       0      65
Bank Sta=996.16,1181.16
XS Rating Curve= 0
Exp/Cntr=.3,.1

Type RM Length L Ch R = 1 ,78754.21,708.88,986.4,248.14
BEGIN DESCRIPTION:
411v32
Bank Station offset =      3902
ROB block at edge of watershed
XS extended on ROB
END DESCRIPTION:
XS GIS Cut Line= 6
     3186761.545    13963622.307     3185326.171    13963622.307
     3184259.892    13964175.952     3183695.995    13964391.258
     3183203.866    13964504.038        3181939.       13964420.
#Sta/Elev= 30
       0   89.71  158.38    85.5   204.3   81.97  446.94    55.5  583.38   45.57
  714.91   48.66  842.33   45.26  979.81   48.93  995.13   47.41 1048.33   47.28
 1054.83   42.88 1060.33   41.62 1063.13   36.78 1078.13   26.78 1098.13   17.88
 1118.13   18.58 1158.13   35.58 1178.13   36.68 1217.53   45.38 1222.13   48.28
 1288.93   54.16  2079.2   49.92  2238.1   51.05 2343.96    57.4 2600.67   53.51
 2854.17   59.91 3293.33   59.08 3599.99   61.35 3881.71   59.86    5019    60.8
#Mann= 3 ,-1 , 0
       0     .12       0 1048.33     .04       0 1222.13     .12       0
#Block Obstruct= 2 , 0
       0                    5014       0      65
Bank Sta=1048.33,1222.13
XS Rating Curve= 0
Exp/Cntr=.3,.1

Type RM Length L Ch R = 1 ,77767.82,991.94,1211.79,528.84
BEGIN DESCRIPTION:
411v33
Bank Station offset =      4426
ROB block at edge of watershed
XS extended on ROB
END DESCRIPTION:
XS GIS Cut Line= 6
     3186925.588    13963007.147     3186028.236    13963022.539
     3184188.123     13963899.13     3183316.646    13964370.753
     3183162.856    13964391.258        3182067.       13964288.
#Sta/Elev= 30
       0   86.46  327.63   90.43  385.89   81.93  448.11    62.5  458.37   51.93
  502.97   42.53  502.97   48.63  508.37   42.53  574.37   17.93  594.37   22.13
  631.37   41.52  656.37   46.13  687.37   47.83  719.37   32.33  730.37   30.93
  762.37   43.13  777.37   45.43  868.69   41.91  961.88   45.86 1089.17   42.16
 1194.69   49.17 1362.52   47.48 1478.35   52.24 1731.93   53.87 2296.43   48.25
  2696.3   54.53  2792.4    51.5 2935.85   52.45 3205.68   60.01    5219    60.8
#Mann= 3 ,-1 , 0
       0     .12       0  502.97     .04       0  777.37     .12       0
#Block Obstruct= 2 , 0
       0                    5214       0      65
Bank Sta=502.97,777.37
XS Rating Curve= 0
Exp/Cntr=.3,.1

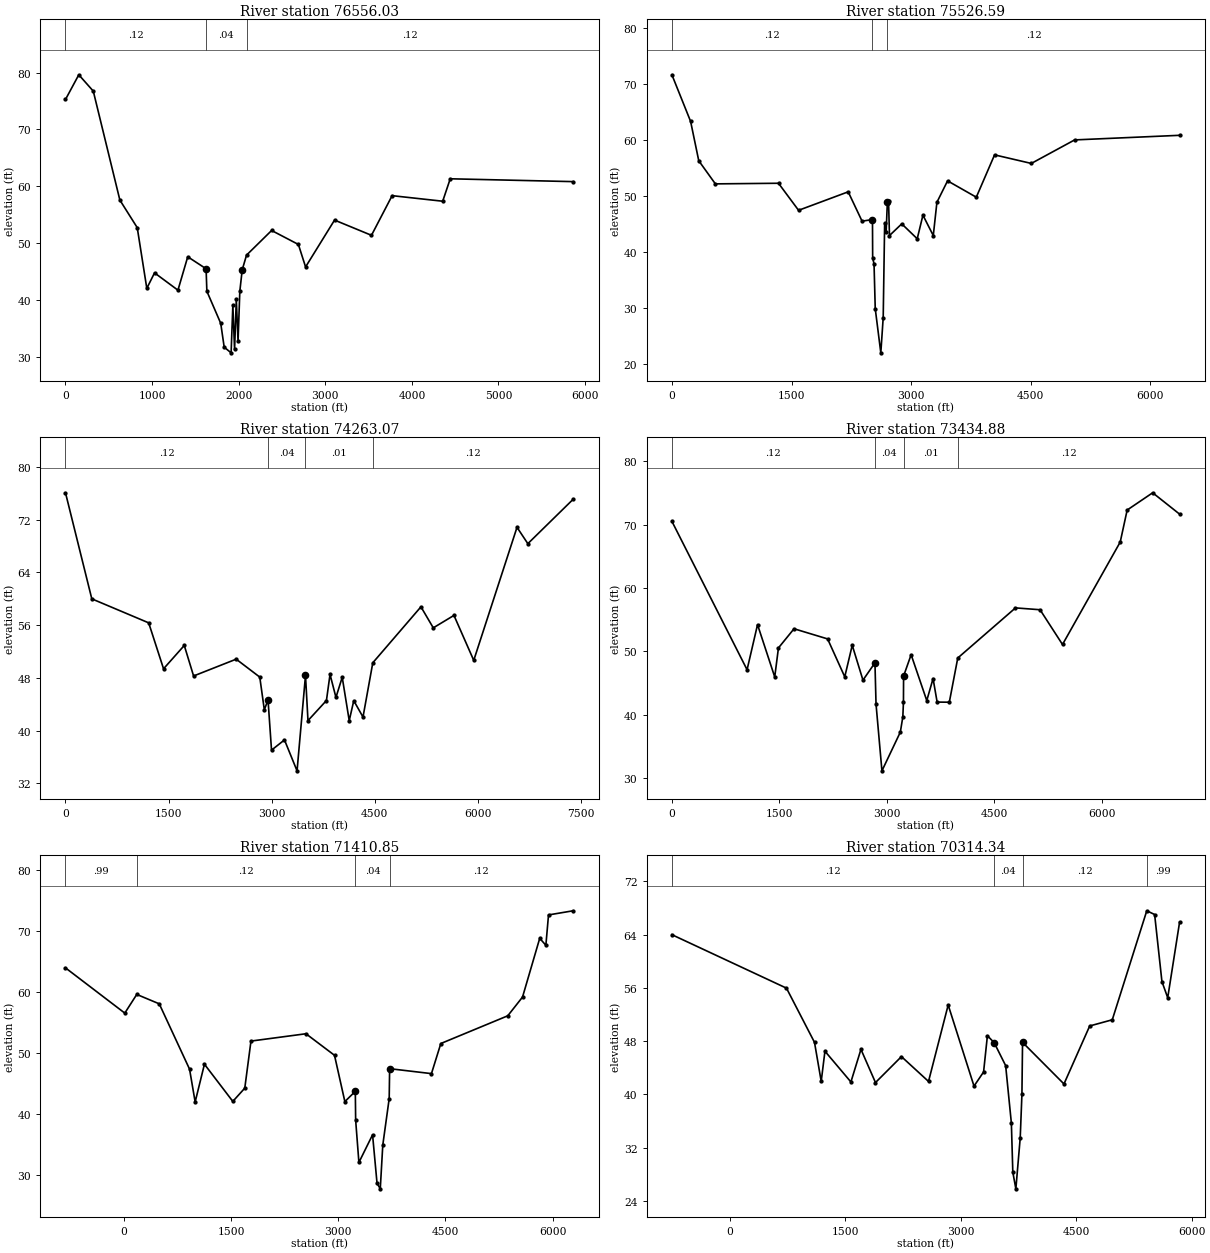
Type RM Length L Ch R = 1 ,76556.03,492.23,1029.44,722.6
BEGIN DESCRIPTION:
411v34
Bank Station offset =      3087
ROB block at edge of watershed
XS extended on ROB
END DESCRIPTION:
XS GIS Cut Line= 6
     3187089.631    13962074.153     3185537.294    13962138.658
     3185080.106    13962822.598     3183183.361     13964206.71
     3182947.549    13964298.984        3182060.       13964214.
#Sta/Elev= 30
       0   75.26  153.76   79.61  321.02   76.73     628   57.55  828.54    52.7
   939.1   42.01 1028.35   44.74 1298.65   41.69 1411.74   47.57 1623.66   45.46
 1632.66    41.5 1792.66   35.86 1832.66   31.66 1912.66   30.66 1932.66   39.06
 1952.66   31.26 1972.66   40.06 1992.66   32.66 2013.16    41.5 2040.66   45.26
 2090.66   47.86 2380.44    52.2 2689.48   49.74 2772.59   45.78 3107.01   54.03
 3533.45   51.35 3771.85   58.33 4355.93   57.35 4442.98    61.3    5862    60.8
#Mann= 3 ,-1 , 0
       0     .12       0 1623.66     .04       0 2090.66     .12       0
#Block Obstruct= 2 , 0
       0                    5857       0      65
Bank Sta=1623.66,2040.66
XS Rating Curve= 0
Exp/Cntr=.3,.1

Type RM Length L Ch R = 1 ,75526.59,545.41,1263.51,3230.45
BEGIN DESCRIPTION:
411v35
Bank Station offset =      2380
ROB block at edge of watershed
XS extended on ROB
END DESCRIPTION:
XS GIS Cut Line= 6
     3187089.631    13961848.594     3186730.787    13961664.046
     3184674.946    13961658.327     3183367.909    13963601.802
     3182937.297    13964104.183 3182051.3468047    13964104.183
#Sta/Elev= 30
       0   71.61  234.74   63.28  336.87   56.26  545.06   52.13 1336.91   52.24
 1588.51   47.41 2210.81   50.71 2384.84   45.47 2515.34   45.76 2517.74   38.86
 2534.94   37.86 2549.94   29.86 2619.94   21.96 2649.94   28.26 2667.94   45.06
 2686.94   43.56 2701.94   48.86 2716.94   49.06  2728.4    42.9  2882.5   44.99
  3076.5   42.33 3148.04   46.54 3277.89    42.9 3323.37   48.84 3457.06   52.67
 3817.45   49.75 4046.43   57.31 4507.33   55.78 5050.65   59.98    6366    60.8
#Mann= 3 ,-1 , 0
       0     .12       0 2515.34     .04       0 2701.94     .12       0
#Block Obstruct= 2 , 0
       0                    6361       0      65
Bank Sta=2515.34,2701.94
XS Rating Curve= 0
Exp/Cntr=.3,.1

Type RM Length L Ch R = 1 ,74263.07,604,828.2,160.11
BEGIN DESCRIPTION:
411v36
Bank Station offset =      1631
ROB block and low Manning's in place to model Caney Creek, a  study  stream.
END DESCRIPTION:
XS GIS Cut Line= 6
     3187500.807    13961472.293      3186981.88    13961167.706
     3184724.004    13961123.014     3184287.248    13960683.885
     3183834.477    13959633.487     3181613.472    13958012.306
#Sta/Elev= 30
       0   76.08  382.86   59.99 1210.18   56.35 1426.55   49.38 1728.05   52.92
 1863.64   48.29 2483.17   50.84 2826.34   48.12 2892.49   43.16 2946.49   44.66
 2997.23   37.04 3185.63   38.59 3368.71    33.9 3491.47   48.37 3527.61   41.52
 3796.17   44.57 3848.37   48.53 3934.48   45.04 4025.77   48.09 4127.66   41.52
 4193.72   44.54 4328.09   42.06 4470.44   50.29 5170.92   58.78 5350.31   55.59
 5651.19   57.48 5939.02   50.66 6568.38   70.84 6726.04   68.36 7384.69   75.09
#Mann= 4 ,-1 , 0
       0     .12       0 2946.49     .04       0 3491.47     .01       0
 4470.44     .12       0
#Block Obstruct= 2 , 0
       0                    3491       0    48.5
Bank Sta=2946.49,3491.47
XS Rating Curve= 0
Exp/Cntr=.3,.1

Type RM Length L Ch R = 1 ,73434.88,1372.43,2024.02,941.44
BEGIN DESCRIPTION:
411v37
Bank Station offset =      2069
ROB block and low Manning's in place to model Caney Creek, a  study stream.
END DESCRIPTION:
XS GIS Cut Line= 6
     3187725.752    13960917.593     3185022.389    13960306.409
     3184598.231    13959869.827     3184044.586    13959644.268
     3182773.254    13958762.538     3181626.872    13957722.942
#Sta/Elev= 30
       0   70.51 1049.09   47.11 1195.18   54.22 1435.24   45.97    1487   50.55
 1704.56   53.57 2173.13   51.97 2412.51   45.99  2516.9   50.97 2666.63   45.47
 2833.95    48.2 2848.95    41.7 2931.39   31.17 3188.22   37.28 3222.97   39.67
 3231.75      42 3233.55   46.11 3338.83   49.48 3557.17   42.25 3645.07   45.72
 3701.76   42.01 3871.83   41.99 3989.75   48.96  4795.4   56.86  5138.1   56.57
 5451.63   51.09 6257.04   67.24 6353.98   72.29 6710.02   75.01 7084.87   71.65
#Mann= 4 ,-1 , 0
       0     .12       0 2833.95     .04       0 3233.55     .01       0
 3989.75     .12       0
#Block Obstruct= 2 , 0
       0                    3340       0    49.1
Bank Sta=2833.95,3233.55
XS Rating Curve= 0
Exp/Cntr=.3,.1

Type RM Length L Ch R = 1 ,71410.85,326.98,1096.52,1809.38
BEGIN DESCRIPTION:
411v38
Bank Station offset =      1412
Extended XS on LOB to elev. 64
END DESCRIPTION:
XS GIS Cut Line= 6
 3187531.840250413960753.0673095     3186412.954    13959408.457
     3184793.031    13958290.915     3183839.532    13958711.275
     3183173.108    13958670.264     3181963.151    13957570.088
#Sta/Elev= 30
    -820      64   10.41   56.59  178.03   59.65  492.98   58.11  917.25   47.41
  995.66   42.04 1125.54   48.22 1523.05   42.13 1690.47    44.3 1777.15   52.01
 2547.14   53.21 2946.83   49.68 3091.75    42.1 3238.28   43.78 3242.91   39.05
 3288.48   32.13 3479.77   36.66  3542.3   28.73 3587.64   27.81 3622.92   34.99
 3712.57   42.59 3718.67   47.49 4304.25   46.68 4435.59   51.61 5372.89   56.15
 5579.59   59.22 5820.31   68.84 5906.35    67.7  5943.4   72.67 6287.92   73.35
#Mann= 4 ,-1 , 0
    -820     .99       0  178.03     .12       0 3238.28     .04       0
 3718.67     .12       0
Bank Sta=3238.28,3718.67
XS Rating Curve= 0
Exp/Cntr=.3,.1

Type RM Length L Ch R = 1 ,70314.34,562.79,1514.5,1987.6
BEGIN DESCRIPTION:
411v39
Bank Station offset =      1282
Extended XS on LOB to elev. 64
No block necessary for ROB.  Flow will be conveyed.
END DESCRIPTION:
XS GIS Cut Line= 6
 3187533.454420613960733.6871378     3186730.787    13959408.457
     3185920.826    13958608.748     3184727.459     13957740.09
     3183695.995    13956158.358     3183262.411    13955842.836
#Sta/Elev= 30
    -750      64  738.17   55.97 1102.21   47.83 1189.36   41.97  1237.8    46.5
 1575.08   41.88 1705.48   46.78 1894.28   41.79 2231.36   45.69 2583.04   41.96
 2838.45   53.44 3173.98   41.26 3298.24   43.38 3347.96   48.83  3435.9   47.78
 3584.81   44.34 3659.15   35.71 3678.01   28.33 3717.56   25.83  3774.1   33.48
 3796.27      40 3804.33   47.83 4342.44   41.58 4676.53   50.29 4969.89   51.22
 5417.96   67.59 5519.93   67.03 5614.78   56.96 5689.92   54.53 5843.36   65.83
#Mann= 4 ,-1 , 0
    -750     .12       0  3435.9     .04       0 3804.33     .12       0
 5417.96     .99       0
Bank Sta=3435.9,3804.33
XS Rating Curve= 0
Exp/Cntr=.3,.1

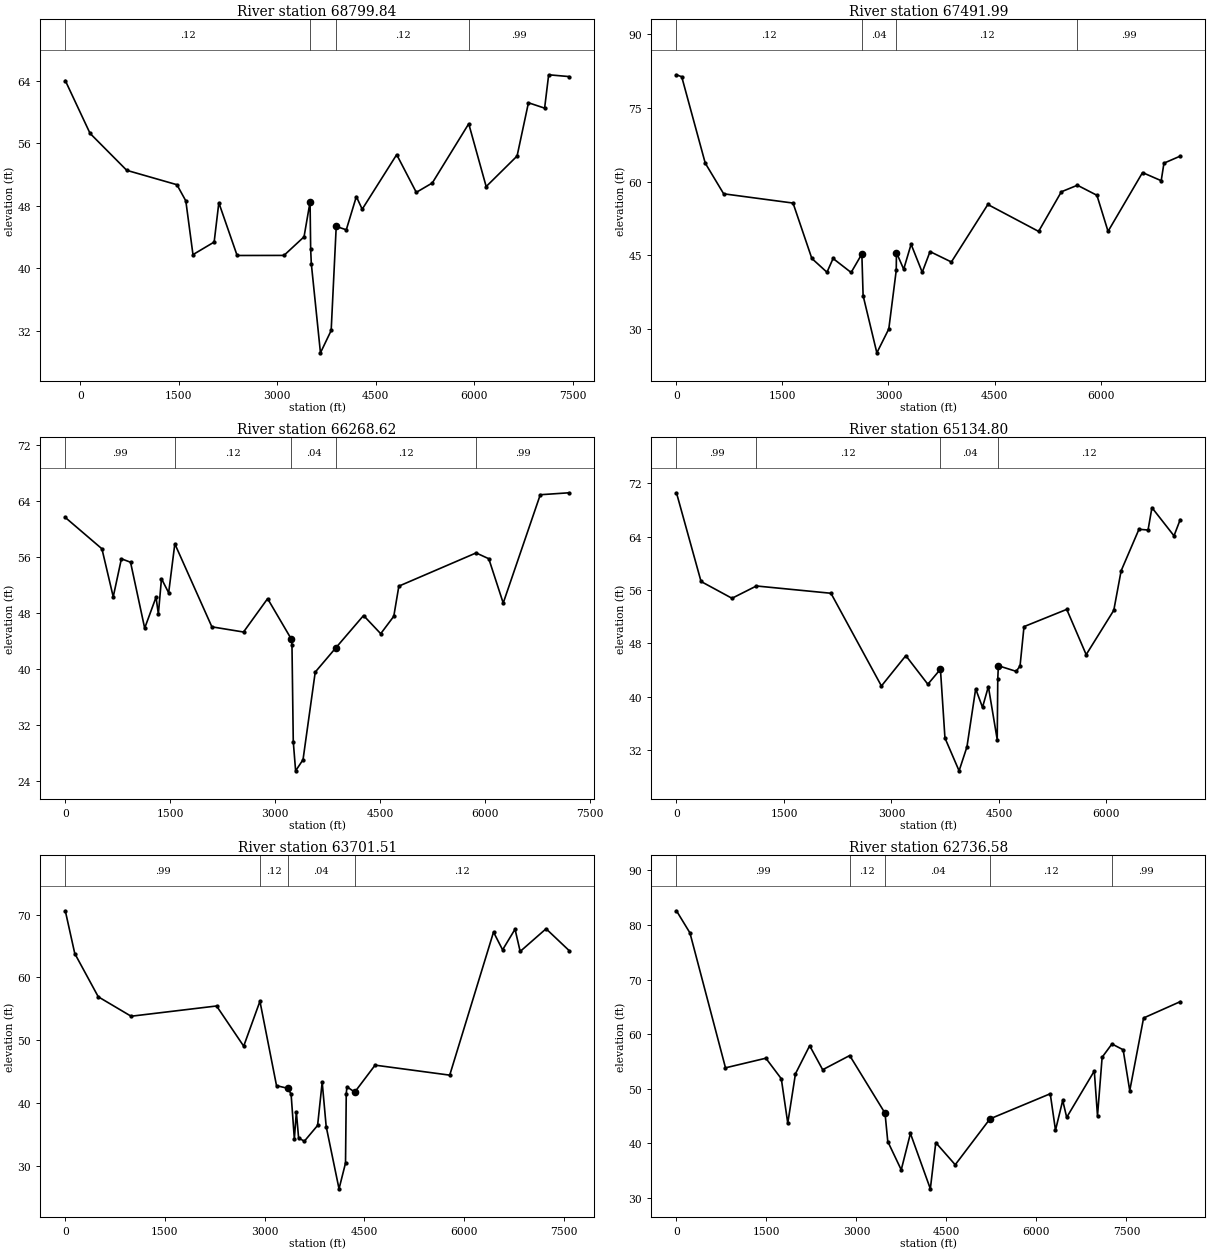
Type RM Length L Ch R = 1 ,68799.84,1535.31,1307.85,488.18
BEGIN DESCRIPTION:
411v40
Bank Station offset =      1342
Extended XS on LOB to elev. 64
No block necessary for ROB.  Flow will be conveyed.
END DESCRIPTION:
XS GIS Cut Line= 6
 3187996.031774113960207.0985207     3185929.542    13957575.968
     3185920.668    13957264.933     3186175.238     13956700.75
     3185807.992    13955577.132     3184862.596    13953578.297
#Sta/Elev= 30
    -230      64   147.2   57.24  706.36   52.51 1470.47   50.67 1606.23    48.6
 1715.27   41.72 2037.96   43.33 2109.29   48.36 2387.95   41.61 3101.55   41.62
 3407.42      44 3499.16   48.47 3508.16   42.47 3518.16   40.57 3657.53   29.15
 3820.75   32.01 3897.77   45.33 4051.17    44.9 4204.38   49.15 4293.49   47.53
 4818.97   54.52 5117.63   49.69 5361.36   50.89 5916.58   58.47  6182.3   50.43
  6653.2   54.34 6826.38   61.16 7072.73   60.47 7134.38   64.74 7445.02   64.51
#Mann= 4 ,-1 , 0
    -230     .12       0 3499.16     .04       0 3897.77     .12       0
 5916.58     .99       0
Bank Sta=3499.16,3897.77
XS Rating Curve= 0
Exp/Cntr=.3,.1

Type RM Length L Ch R = 1 ,67491.99,1643.24,1223.36,433.63
BEGIN DESCRIPTION:
411v46
Bank Station offset =      2165
No block necessary for ROB.  Flow will be conveyed.
END DESCRIPTION:
XS GIS Cut Line= 4
     3189412.006    13959075.635     3187810.021    13957607.149
      3186875.53    13956966.355     3185113.347    13953575.487
#Sta/Elev= 30
       0   81.67    74.3   81.27  407.28   63.73  667.88   57.51 1649.34   55.63
 1915.33   44.39 2129.47   41.59 2216.11   44.38 2471.22   41.54    2623   45.29
  2640.8   36.85 2835.19   25.23 3004.23   30.08 3109.59   41.97 3112.41   45.59
 3214.88    42.2 3319.79   47.27 3477.19   41.59 3587.91   45.78 3889.67   43.67
 4405.66   55.34 5123.81   49.88 5445.84   57.92 5672.85   59.25 5949.05   57.21
 6106.42   49.89 6594.32   61.82 6858.67   60.17 6897.35   63.73 7127.71   65.16
#Mann= 4 ,-1 , 0
       0     .12       0    2623     .04       0 3112.41     .12       0
 5672.85     .99       0
Bank Sta=2623,3112.41
XS Rating Curve= 0
Exp/Cntr=.3,.1

Type RM Length L Ch R = 1 ,66268.62,853.85,1133.82,1197.58
BEGIN DESCRIPTION:
411v41
Bank Station offset =      1707
LOB block due to a laterial stream causing no conveyance
No block necessary for ROB.  Flow will be conveyed.
END DESCRIPTION:
XS GIS Cut Line= 6
     3190494.451    13957913.609     3189116.875    13956454.999
     3187152.238    13955957.679     3186672.353    13955712.189
     3185956.554     13954807.31     3185295.371    13953504.168
#Sta/Elev= 30
       0   61.67  523.73   57.19  685.36   50.32  802.16   55.76  932.79   55.27
 1135.03   45.84 1297.34   50.27 1330.56   47.87 1375.07   52.91 1477.85    50.9
 1565.89    57.9 2095.81   46.03    2548   45.29 2892.41   50.06 3233.66   44.24
  3240.8   43.39 3259.24   29.62 3292.86   25.44  3398.7   27.03 3573.22   39.56
 3866.89   43.02 4264.15   47.65 4509.36   45.05 4696.23   47.54 4768.65   51.85
 5873.12    56.6 6054.39   55.77 6260.66   49.43 6790.44   64.92 7201.92    65.2
#Mann= 5 ,-1 , 0
       0     .99       0 1565.89     .12       0 3233.66     .04       0
 3866.89     .12       0 5873.12     .99       0
Bank Sta=3233.66,3866.89
XS Rating Curve= 0
Exp/Cntr=.3,.1

Type RM Length L Ch R = 1 ,65134.80,1085.04,1433.29,1199.27
BEGIN DESCRIPTION:
411v47
Bank Station offset =      1056
No block necessary for ROB.  Flow will be conveyed.
END DESCRIPTION:
XS GIS Cut Line= 6
     3190933.892     13957500.35     3189492.105    13955738.166
     3188210.518    13955097.372     3187436.225    13954803.675
     3186822.131    13954429.879     3185407.044    13953361.889
#Sta/Elev= 30
       0   70.54  343.03   57.27  774.85   54.76 1115.46    56.6 2155.76   55.51
    2860   41.64 3200.48   46.18  3507.8    41.9 3683.52   44.15 3746.58   33.86
 3943.81   28.95 4053.32   32.53 4175.16   41.21 4270.69   38.45 4352.42   41.56
 4475.89   33.61 4483.53   42.69 4491.82   44.67  4740.4   43.83 4794.27   44.63
 4849.63   50.52 5446.09    53.1 5717.29   46.33 6102.42   52.96 6204.77   58.86
  6453.7   65.08 6580.68   64.97 6634.73   68.32 6942.84    64.1 7029.61   66.53
#Mann= 4 ,-1 , 0
       0     .99       0 1115.46     .12       0 3683.52     .04       0
 4491.82     .12       0
Bank Sta=3683.52,4491.82
XS Rating Curve= 0
Exp/Cntr=.3,.1

Type RM Length L Ch R = 1 ,63701.51,1030.87,964.92,1706.73
BEGIN DESCRIPTION:
411v42
Bank Station offset =       880
END DESCRIPTION:
XS GIS Cut Line= 6
     3191195.541    13957019.813     3190649.865     13956385.73
     3189259.914    13954440.978     3188496.829    13953641.307
     3187469.186    13953416.229     3185294.777    13953173.127
#Sta/Elev= 30
       0    70.6   142.7    63.8  496.33   56.92   990.6   53.83  2277.1   55.46
 2685.37   49.07 2929.84   56.21 3179.45   42.79 3351.53   42.36 3398.91   41.43
 3447.85   34.32 3477.94   38.61 3511.76   34.48 3597.94   33.95 3797.64   36.46
 3866.84   43.33 3926.93   36.29 4120.37   26.38    4218   30.48 4229.23   41.52
 4239.19   42.61  4356.7   41.76 4663.32   46.05 5786.48   44.46 6445.78   67.21
  6582.2   64.39 6769.56   67.67 6846.84   64.13 7236.82   67.74 7582.65   64.28
#Mann= 4 ,-1 , 0
       0     .99       0 2929.84     .12       0 3351.53     .04       0
  4356.7     .12       0
Bank Sta=3351.53,4356.7
XS Rating Curve= 0
Exp/Cntr=.3,.1

Type RM Length L Ch R = 1 ,62736.58,1387.46,1246.21,1087.8
BEGIN DESCRIPTION:
411v48
Bank Station offset =       768
END DESCRIPTION:
XS GIS Cut Line= 5
     3192028.582    13956245.462     3189785.803    13953575.487
     3188557.614    13952293.899     3187649.823    13951439.507
      3185780.84    13951172.509
#Sta/Elev= 30
       0    82.6  224.43   78.55  817.21   53.83 1489.97   55.59 1747.39   51.83
 1855.17   43.69 1983.39   52.74 2220.08   57.88 2437.01   53.48 2887.42   56.08
  3476.2   45.52 3522.04   40.33 3746.46   35.14  3899.7   41.81 4231.57   31.66
 4322.18   40.13 4646.15   36.07 5226.03   44.48 6230.09   49.08 6317.64    42.4
    6438   47.86 6504.19   44.75 6964.35   53.25 7017.72   45.03 7095.01   55.77
 7258.35    58.2 7445.17   57.14 7555.21   49.65 7785.97   62.96 8396.61   65.95
#Mann= 5 ,-1 , 0
       0     .99       0 2887.42     .12       0  3476.2     .04       0
 5226.03     .12       0 7258.35     .99       0
Bank Sta=3476.2,5226.03
XS Rating Curve= 0
Exp/Cntr=.3,.1

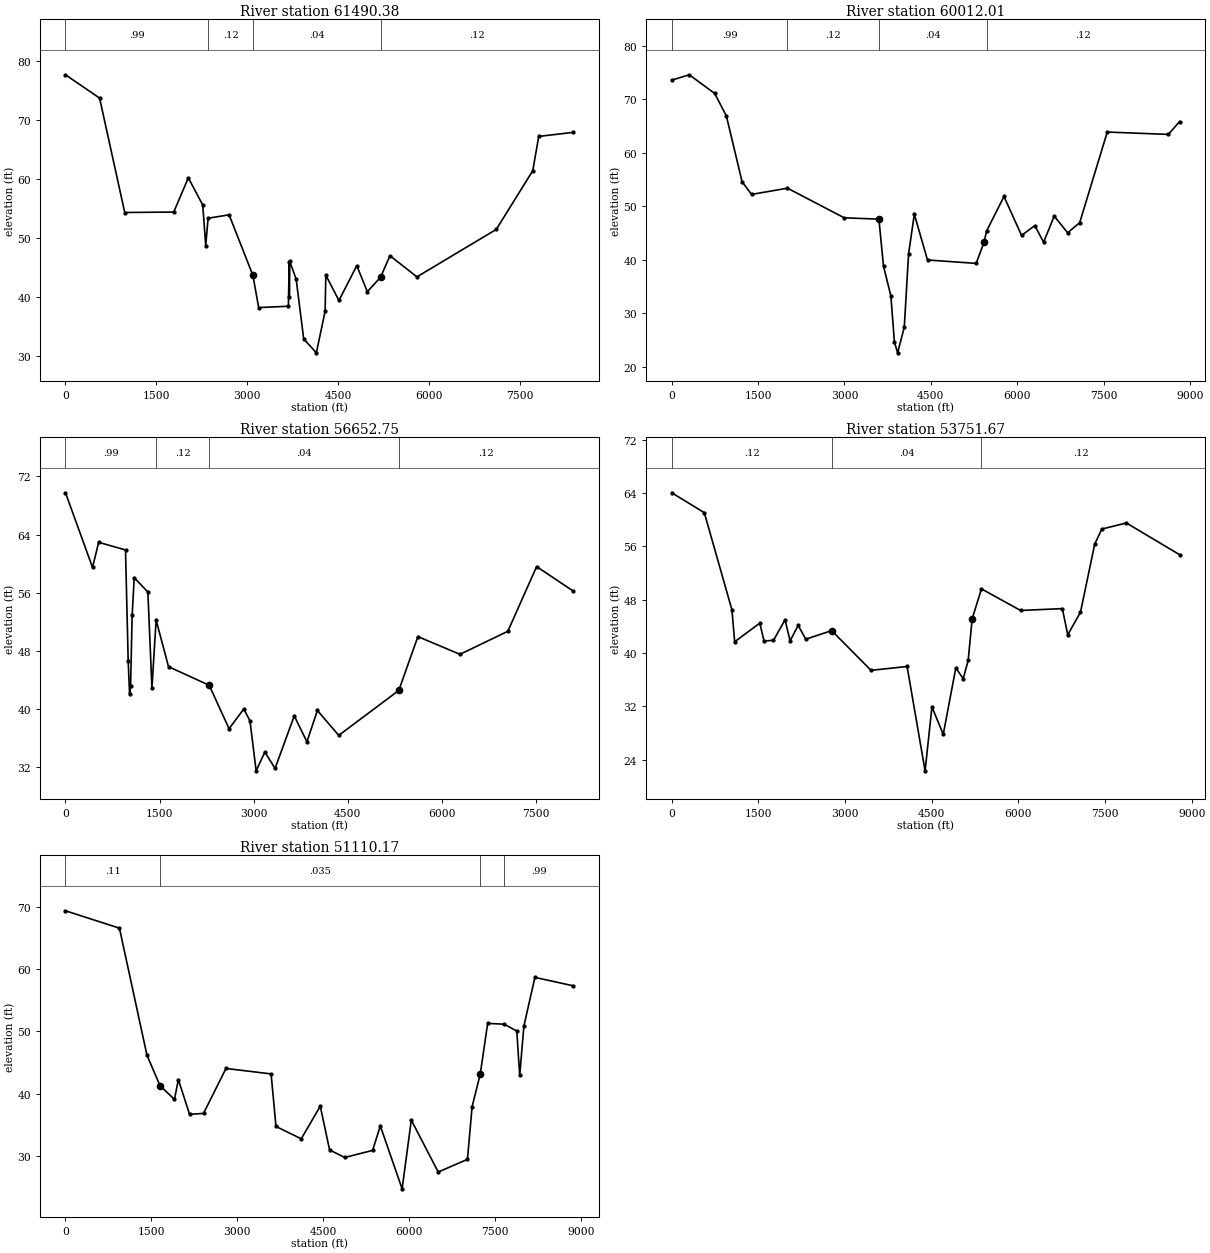
Type RM Length L Ch R = 1 ,61490.38,2166.85,1478.37,1399.14
BEGIN DESCRIPTION:
411v49
Bank Station offset =       862
END DESCRIPTION:
XS GIS Cut Line= 5
     3192989.772    13955631.367     3191334.388    13953548.787
      3191094.09    13953148.291     3189598.904    13951599.705
     3186982.329    13949944.321
#Sta/Elev= 30
       0   77.66  562.41   73.71  977.14   54.31 1785.45   54.39 2026.09   60.19
 2263.36   55.59 2313.35    48.7 2351.67   53.34 2698.65   53.92 3090.84   43.67
 3186.51   38.19 3676.54   38.42 3690.14   45.94 3691.77   40.05  3698.6   46.04
 3804.56   43.01 3929.21   32.88 4137.83   30.52 4282.85    37.6 4293.57   43.69
 4510.19    39.4 4804.88    45.3 4978.77   40.89 5197.03   43.33 5351.51   46.99
 5796.78    43.4 7105.87   51.45 7707.38    61.4 7805.73   67.21 8376.25    67.9
#Mann= 4 ,-1 , 0
       0     .99       0 2351.67     .12       0 3090.84     .04       0
 5197.03     .12       0
Bank Sta=3090.84,5197.03
XS Rating Curve= 0
Exp/Cntr=.3,.1

Type RM Length L Ch R = 1 ,60012.01,3379.11,3359.26,3377.72
BEGIN DESCRIPTION:
411v43
Bank Station offset =      1077
END DESCRIPTION:
XS GIS Cut Line= 6
     3194695.901    13954192.011     3191908.592     13951937.06
     3190527.312     13950700.62     3189197.909    13949729.187
     3188745.575    13949382.719     3187848.035    13948643.406
#Sta/Elev= 30
       0    73.6  304.43    74.6  746.54   71.11   949.1   66.91 1221.82   54.62
 1385.79   52.25 2010.41   53.41 2995.72   47.88 3597.91   47.63 3677.74   38.83
 3806.03   33.28 3867.01   24.67 3923.26   22.65 4038.67   27.46 4112.95   41.12
 4212.92   48.54 4441.82      40 5286.21   39.36 5424.05   43.31 5467.41   45.41
 5770.05   51.86 6074.96   44.59 6304.84   46.42 6457.67   43.32  6642.2   48.19
 6875.51   45.08 7084.35   46.96 7563.37    63.9  8624.3   63.46 8818.41   65.85
#Mann= 4 ,-1 , 0
       0     .99       0 2010.41     .12       0 3597.91     .04       0
 5467.41     .12       0
Bank Sta=3597.91,5424.05
XS Rating Curve= 0
Exp/Cntr=.3,.1

Type RM Length L Ch R = 1 ,56652.75,4557.88,2901.08,1935.55
BEGIN DESCRIPTION:
411v44
Bank Station offset =      1958
ROB block at end of section
END DESCRIPTION:
XS GIS Cut Line= 6
     3195674.167    13951990.912     3194861.047    13950025.574
     3192321.045    13948014.127     3191723.465    13947622.307
     3190675.438     13946993.35      3190033.85    13946518.733
#Sta/Elev= 30
       0   69.75  431.09   59.48  529.27   62.93  957.54   61.88 1000.42   46.57
 1022.42   42.06 1038.64   43.18 1063.35    52.9 1096.98   58.06 1314.39   56.08
 1379.27   42.86    1446   52.23 1643.73   45.81 2293.09   43.25 2610.02   37.27
 2844.72   39.98  2943.7   38.36 3041.84   31.47 3181.64   34.06 3343.48    31.8
 3650.04   39.03 3852.46   35.47 4019.07   39.78 4359.92   36.35 5318.18   42.54
 5622.98   49.95 6294.76   47.51 7057.69   50.68 7517.41   59.59 8102.81   56.21
#Mann= 4 ,-1 , 0
       0     .99       0    1446     .12       0 2293.09     .04       0
 5318.18     .12       0
#Block Obstruct= 2 , 0
       0                 7729.74       0   60.37
Bank Sta=2293.09,5318.18
XS Rating Curve= 0
Exp/Cntr=.3,.1

Type RM Length L Ch R = 1 ,53751.67,3538.7,2641.5,2871.44
BEGIN DESCRIPTION:
411v50
Bank Station offset =       614
Block added to close cross section
END DESCRIPTION:
XS GIS Cut Line= 6
     3198943.816    13947087.448      3197528.73    13946953.949
     3196273.842    13946633.552     3193790.765     13946847.15
     3192055.281    13946713.651     3190293.098    13946179.656
#Sta/Elev= 30
       0   64.04  564.17   61.06  1042.8   46.47 1089.54   41.69 1524.82   44.49
 1597.53   41.81 1761.57   41.92 1961.46   44.99 2049.45   41.83 2189.11   44.16
 2320.38   42.08 2769.07   43.37 3449.99   37.41 4074.56   37.99 4385.92   22.34
 4504.73   31.93 4700.57   27.81 4917.83   37.78 5046.59   36.16 5132.12   38.92
 5201.15   45.15 5362.32   49.63 6038.73   46.39  6762.2   46.67 6855.59   42.74
 7075.82   46.12 7322.08   56.33 7444.47    58.6 7870.45   59.51 8790.69   54.76
#Mann= 3 ,-1 , 0
       0     .12       0 2769.07     .04       0 5362.32     .12       0
#Block Obstruct= 2 , 0
       0                 7625.81       0   59.49
Bank Sta=2769.07,5201.15
XS Rating Curve= 0
Exp/Cntr=.3,.1

Type RM Length L Ch R = 1 ,51110.17,0,0,0
BEGIN DESCRIPTION:
411v45
This is a common section for EF San jacincto and lake Houston. The boundary condition is applied based on the WSELs obtained at this cross section from the Lake Houston model
Bank Station offset =      -877
END DESCRIPTION:
XS GIS Cut Line= 6
     3198991.102    13943369.938     3197746.983    13943408.545
     3197355.319    13943489.579     3191804.499    13945015.717
     3191187.013    13945224.865     3190584.124    13945769.748
#Sta/Elev= 30
       0   69.36  941.98   66.57 1421.32   46.22 1649.12   41.31 1902.72   39.09
 1970.34   42.27 2166.07    36.7 2409.52   36.84 2802.27   44.06 3590.06   43.18
 3674.79   34.75 4115.96   32.77 4448.14      38 4610.96   30.98 4874.73   29.77
 5361.49   30.91 5496.89   34.83  5877.3   24.74 6037.54   35.77 6507.63   27.44
 7017.81   29.47 7099.32   37.94 7241.44   43.15 7370.81   51.29 7658.04   51.16
 7878.97   50.07 7930.38   42.95 8003.35   50.85 8195.34   58.67 8866.25   57.32
#Mann= 4 ,-1 , 0
       0     .11       0 1649.12    .035       0 7241.44     .11       0
 7658.04     .99       0
Bank Sta=1649.12,7241.44
XS Rating Curve= 0
Exp/Cntr=.3,.1

Chan Stop Cuts=-1